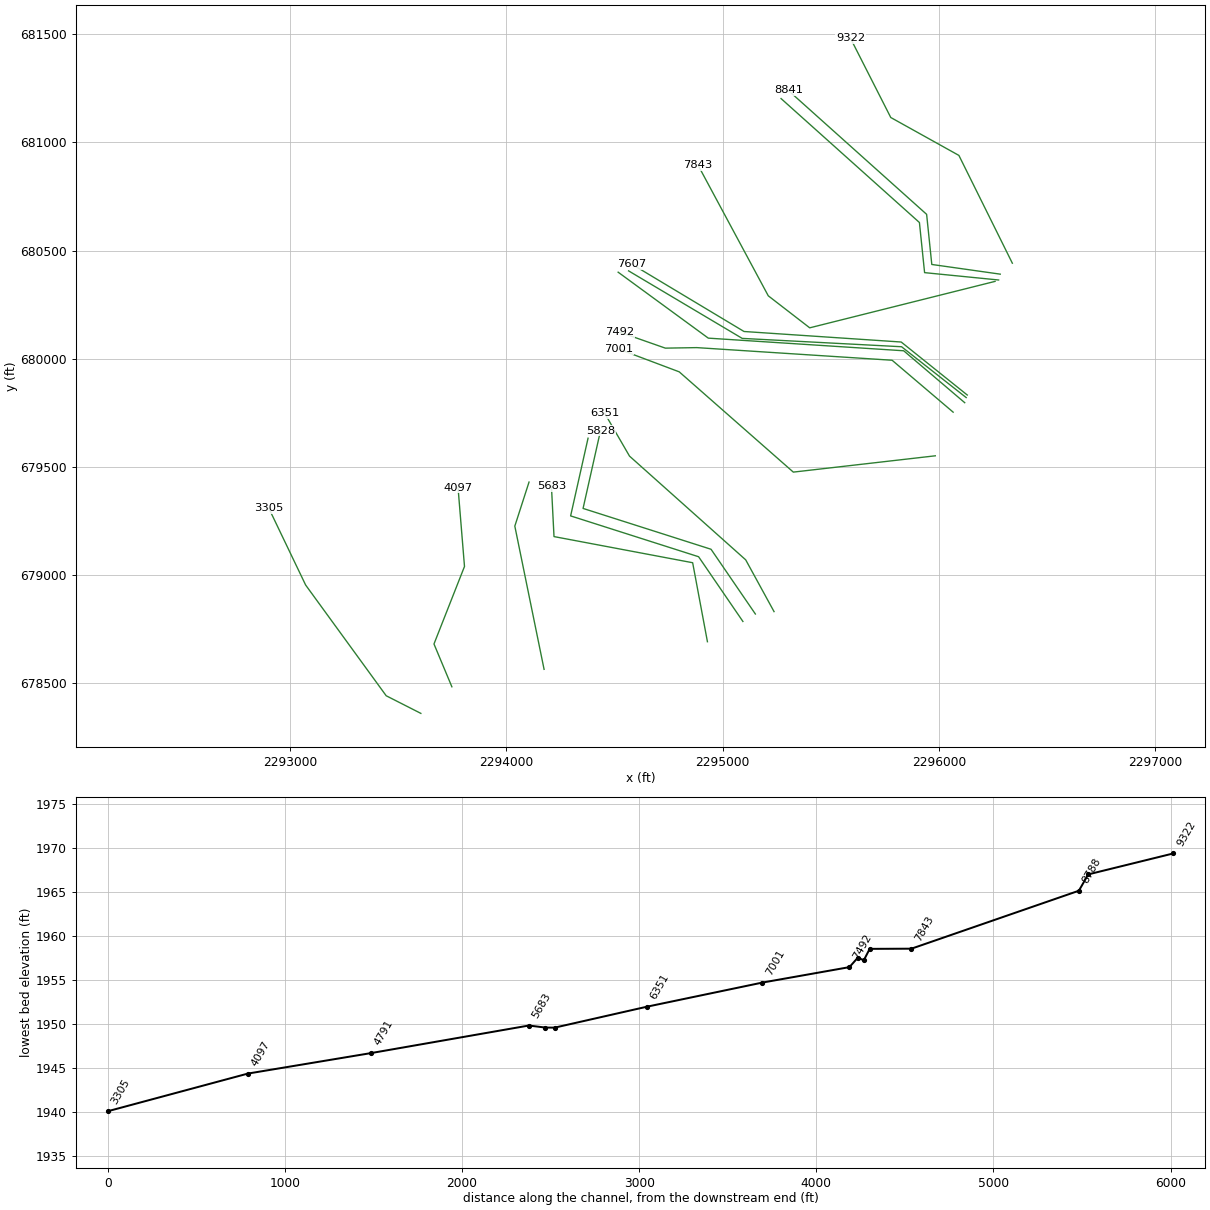
HEC-RAS study KINGSRN.prj: KINGSRN

--- KINGSRN.g01 (geometry) --- (continued)

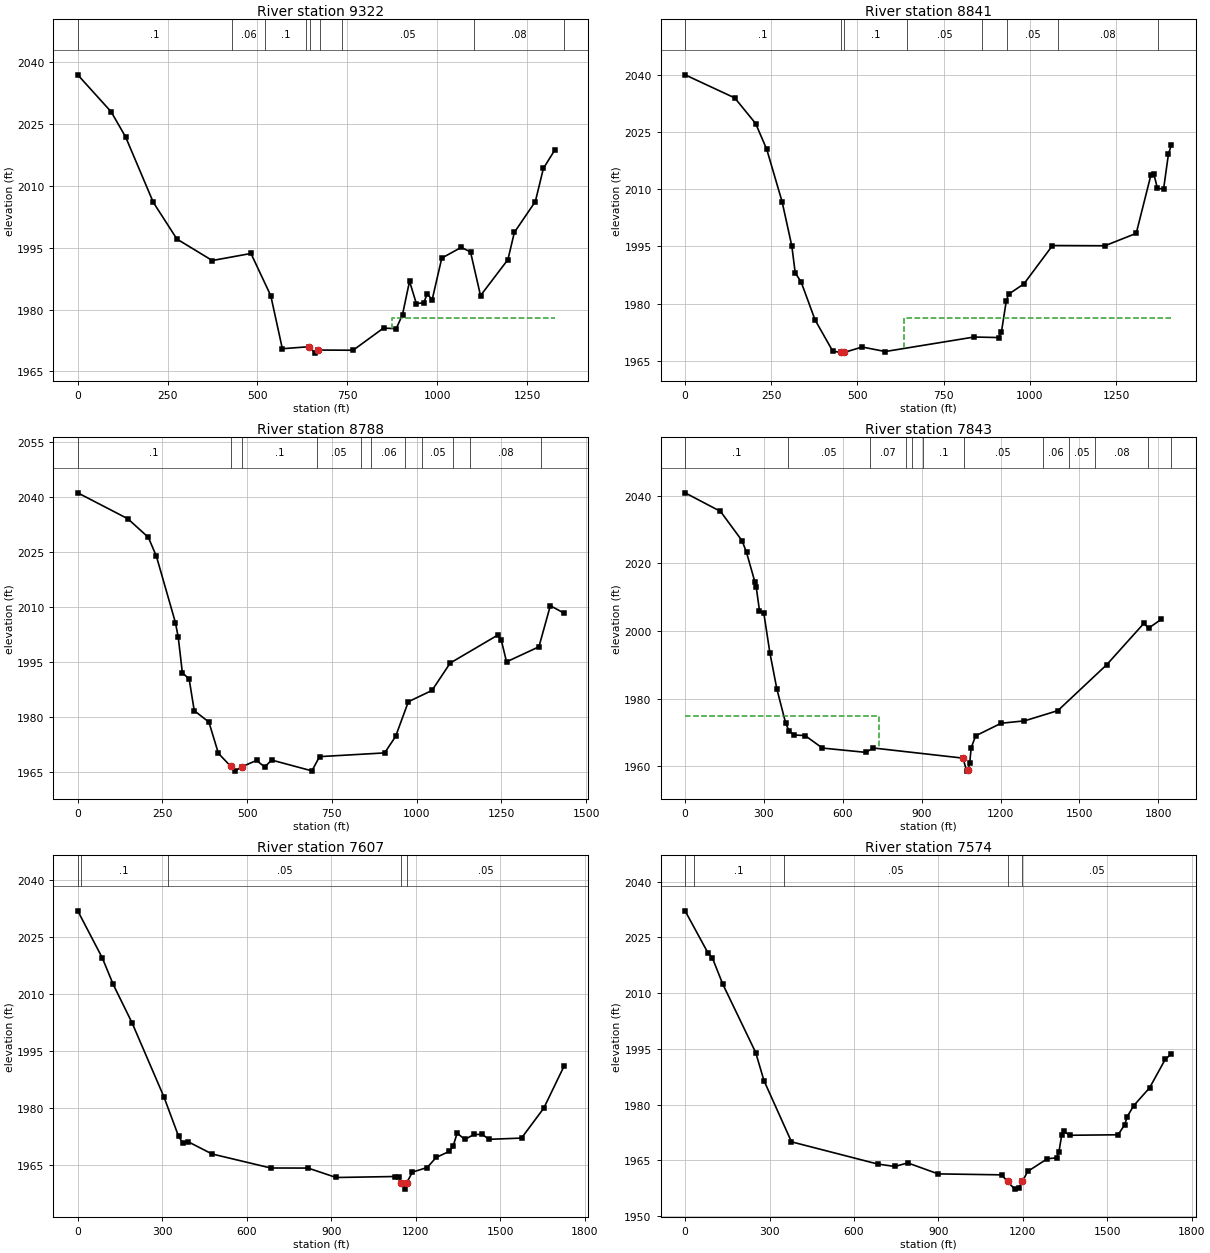
Type RM Length L Ch R = 1 ,9322    ,463.4,481.1,460.5
XS GIS Cut Line= 4
2296338.69936703680441.9423668862296091.74900416680940.020333619
 2295776.8342917681115.2538889712295590.80684039681481.125265324
#Sta/Elev= 30
       0 2036.93    92.9 2027.97   133.1 2021.88   210.2    2006   275.9  1997.1
   374.2 1991.89   481.9  1993.6     537 1983.36   569.2  1970.5   643.11970.984
   660.7 1969.43   669.71970.177     766 1970.13   850.6 1975.51   885.9 1975.35
   903.5 1978.79     923 1986.87     942 1981.43   962.9 1981.66   972.3 1983.88
   985.8 1982.33  1012.7 1992.48    1067 1995.09  1092.7 1993.96  1120.5 1983.38
  1196.7 1992.12  1214.6 1998.71    1273  2006.2  1295.4 2014.24  1326.8 2018.65
#Mann= 9 ,-1,0
       0      .1       0     430     .06       0     520      .1       0
  635.94     .07       0  647.24    .045       0   674.2     .07       0
  735.94     .05       0 1103.02     .08       0 1353.02     .06       0
#XS Ineff= 2 , 0
                           875.3         1977.98
Permanent Ineff=
       F       F
Bank Sta=643.1,669.7
XS Rating Curve= 0 ,0
Exp/Cntr(USF)=0,0
Exp/Cntr=0.3,0.1

Type RM Length L Ch R = 1 ,8841    ,69.5,52.8,50.6
XS GIS Cut Line= 4
2296282.85777089680391.2552619592295966.46749173  680436.0647766
2295942.57541695680667.7346745342295303.12816018681240.543303662
#Sta/Elev= 30
       0 2039.95   144.1  2033.9   204.7 2027.19     237 2020.41   281.5 2006.68
   309.7 1995.07   319.5 1988.08   336.8 1985.65     377 1975.75   428.4 1967.55
  450.971967.229   457.2 1967.04  461.841967.229   513.7 1968.64   580.7 1967.46
   838.4 1971.26   909.3 1971.12   917.8 1972.65   931.6 1980.62   938.3 1982.47
   982.9 1985.18  1065.8 1995.23    1218 1995.17  1308.7 1998.42  1351.2 2013.67
  1359.7 2014.06  1369.9 2010.29    1388 2009.98  1402.1 2019.15  1410.9 2021.67
#Mann= 8 ,-1,0
       0      .1       0  450.97    .045       0  461.84      .1       0
  642.45     .05       0  862.45     .06       0  932.45     .05       0
 1082.45     .08       0 1372.45     .06       0
#XS Ineff= 2 , 0
                           636.1         1976.18
Permanent Ineff=
       F       F
Bank Sta=450.97,461.84
XS Rating Curve= 0 ,0
Exp/Cntr(USF)=0,0
Exp/Cntr=0.3,0.1

Type RM Length L Ch R = 1 ,8788    ,922.2,945.3,943.6
XS GIS Cut Line= 4
2296275.33084177680364.3102170062295933.17086339 680398.26933198
2295909.27878862680629.9392299132295269.83153184681202.747859042
#Sta/Elev= 30
       0 2041.24   147.9 2034.15   208.5 2029.05   232.3 2023.85   288.2 2005.79
   296.6 2001.76   308.7 1992.09   328.8 1990.32   343.8 1981.71     387 1978.59
   415.1 1970.03   451.3 1966.52   463.4 1965.18   485.9 1966.44   527.7 1968.11
   551.8  1966.3     572 1968.21     691 1965.25   713.5 1969.14   905.6 1970.16
     938 1974.67   975.6 1984.15  1045.4 1987.24  1099.1 1994.72  1239.8 2002.38
  1249.5 2001.09  1265.3 1995.05  1360.9 1999.16  1394.5 2010.39  1435.2 2008.35
#Mann= 11 ,-1,0
       0      .1       0   451.3    .045       0   485.9      .1       0
  706.74     .05       0  836.74      .1       0  866.74     .06       0
  966.74      .1       0 1016.74     .05       0 1106.74      .1       0
 1156.74     .08       0 1366.74      .1       0
Bank Sta=451.3,485.9
XS Rating Curve= 0 ,0
Exp/Cntr(USF)=0,0
Exp/Cntr=0.3,0.1

Type RM Length L Ch R = 1 ,7843    ,232.4,235.6,234.9
XS GIS Cut Line= 4
2296258.84619441680357.8573767322295402.24939606 680143.21075771
2295210.73334527680291.179978516 2294885.7360234680895.734093589
#Sta/Elev= 30
       0 2040.87   134.7 2035.38   217.1 2026.67   233.7 2023.25   266.1 2014.36
   270.8 2012.88     283 2006.06   299.7 2005.19   322.6 1993.56   349.1 1982.88
   382.1 1972.93   394.5 1970.57   414.9 1969.26   456.4  1969.1   522.3  1965.4
   687.3 1964.13   716.1 1965.42    10571962.422  1071.3 1958.58  1076.6 1958.95
  1082.6 1960.97  1088.4 1965.53  1105.5 1969.03  1202.3 1972.74    1291 1973.44
    1418 1976.47    1604 1990.06    1745 2002.26  1763.2 2000.86  1811.5 2003.47
#Mann= 12 ,-1,0
       0      .1       0     390     .05       0  704.52     .07       0
   839.6    .045       0  863.02     .07       0  904.52      .1       0
 1060.07     .05       0 1360.07     .06       0 1460.07     .05       0
 1560.07     .08       0 1760.07      .1       0 1850.07     .06       0
#XS Ineff= 2 , 0
          737.54 1974.98
Permanent Ineff=
       F       F
Bank Sta=1057,1076.6
XS Rating Curve= 0 ,0
Exp/Cntr(USF)=0,0
Exp/Cntr=0.3,0.1

Type RM Length L Ch R = 1 ,7607    ,34.4,33.3,41
XS GIS Cut Line= 4
2296130.39807338 679832.696797182295825.06905872680077.631061688
2295098.65442494  680126.28238822294578.58852085680438.321930655
#Sta/Elev= 30
       0 2031.78    87.3 2019.37   125.9 2012.41   192.6 2002.34   305.4 1982.91
   357.6 1972.51   371.8  1970.8   392.3 1971.01   476.5 1967.81     685 1964.12
   817.3  1964.1   917.1 1961.62    1127 1961.88  1140.7 1961.67 1148.111960.176
  1159.7 1958.56  1167.1 1960.18  1187.5 1963.03    1240 1964.24  1272.1  1966.9
  1318.7  1968.5  1332.3 1969.88  1346.3 1973.29  1373.9 1971.63  1406.2 1972.95
  1436.1 1972.95  1458.7 1971.66  1574.8 1971.99  1653.8 1979.86    1726 1990.95
#Mann= 5 ,-1,0
       0     .05       0      10      .1       0     320     .05       0
 1148.11    .045       0  1167.1     .05       0
Bank Sta=1148.11,1167.1
XS Rating Curve= 0 ,0
Exp/Cntr(USF)=0,0
Exp/Cntr=0.3,0.1

Type RM Length L Ch R = 1 ,7574    ,24.2,33.7,48.6
XS GIS Cut Line= 4
2296125.36517754679820.9533735392295826.74669067680055.821846355
 2295090.2662652680094.4073811752294565.16746526 680406.44692363
#Sta/Elev= 30
       0 2032.12    80.8 2020.87    97.4 2019.36   133.8 2012.43   250.9 1994.01
   280.2 1986.47   378.1 1969.98   684.3 1964.01   745.2 1963.35   791.2 1964.31
   899.2 1961.36  1124.5  1961.1 1145.651959.326    1171 1957.26    1185 1957.59
  1198.9 1959.34  1217.3 1962.02  1287.3 1965.44  1319.9 1965.67  1328.2 1967.17
  1338.5 1971.92  1344.8 1972.86  1366.4 1971.75  1538.3 1971.88  1561.7 1974.53
  1571.2 1976.78  1594.4 1979.74  1650.3 1984.49  1706.1 1992.16  1728.2 1993.68
#Mann= 5 ,-1,0
       0     .05       0      30      .1       0     350     .05       0
 1145.65    .045       0  1198.9     .05       0
Bank Sta=1145.65,1198.9
XS Rating Curve= 0 ,0
Exp/Cntr(USF)=0,0
Exp/Cntr=0.3,0.1

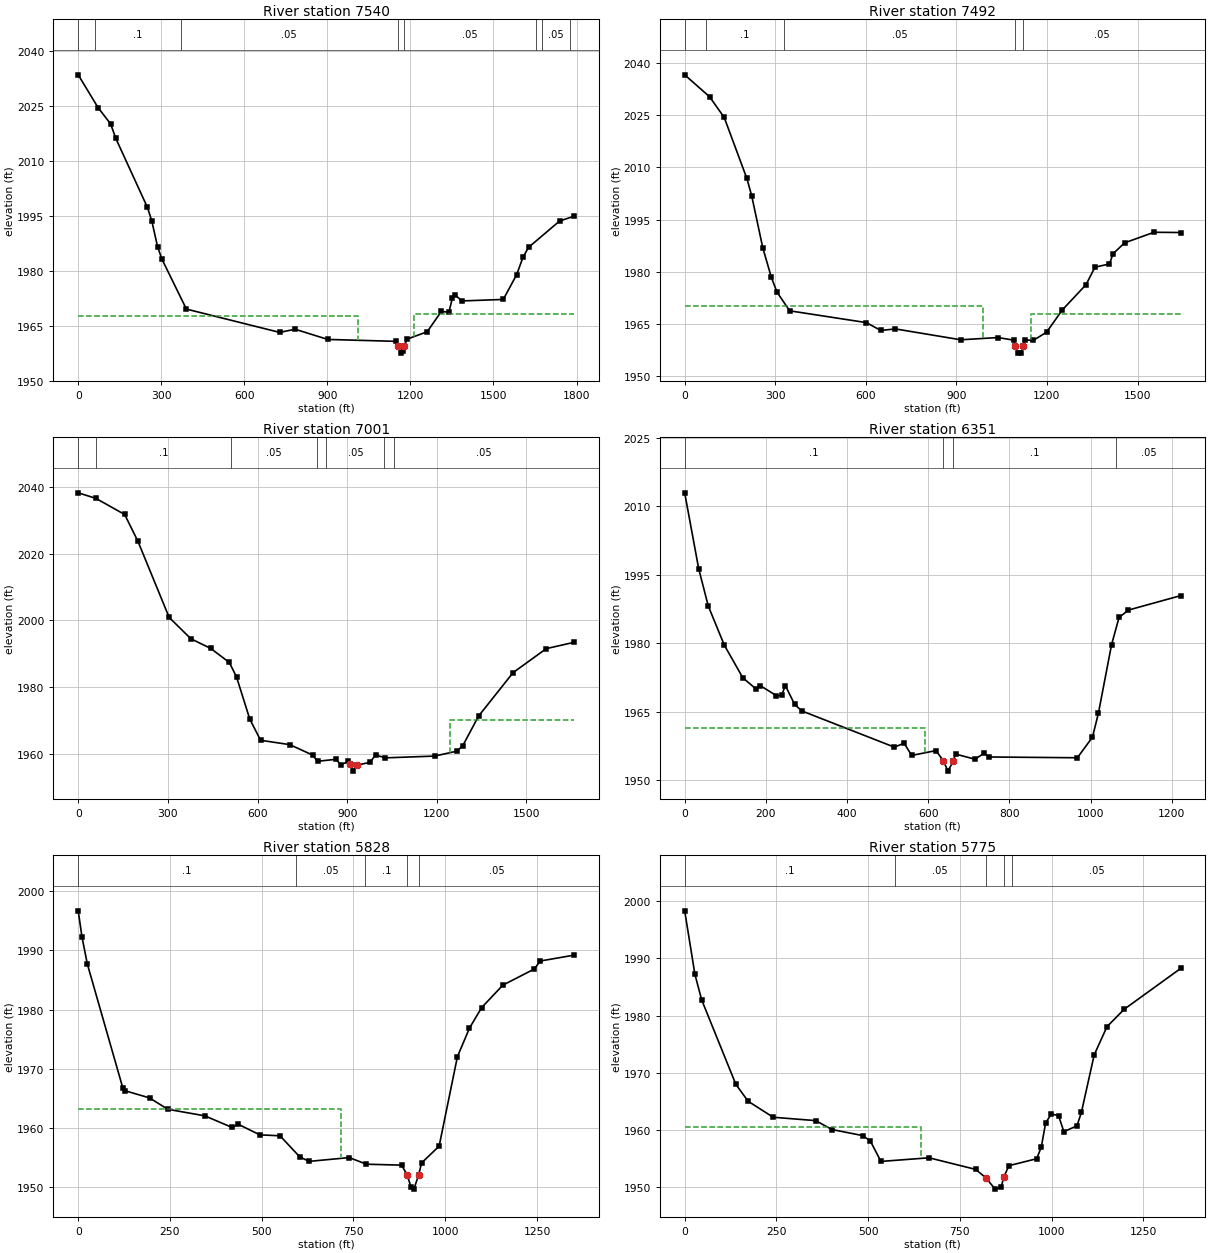
Type RM Length L Ch R = 1 ,7540    ,47.8,47.4,47.5
XS GIS Cut Line= 4
2296118.61051816679797.2657132022295836.53596114680037.191198476
2294933.57315508 680095.551451652294516.94579214680400.321662674
#Sta/Elev= 30
       0 2033.39    71.5 2024.48   117.2 2019.99   135.7 2016.08     250 1997.27
   265.8 1993.57   286.8  1986.5   302.5 1983.15   390.7 1969.56   727.4 1963.21
   783.5 1964.07   901.5 1961.29  1148.3 1960.77  1154.41959.464  1164.3 1957.56
  1172.1 1958.08  1176.3 1959.47  1188.4 1961.38  1260.5 1963.38  1311.8 1968.93
  1338.9  1968.7  1351.2 1972.45  1360.3 1973.48  1386.1 1971.78  1535.4 1972.19
  1583.6 1978.92  1606.5 1983.66  1626.5 1986.37  1738.6 1993.54  1791.4 1994.88
#Mann= 8 ,-1,0
       0     .05       0      60      .1       0     370     .05       0
  1154.4    .045       0  1176.3     .05       0 1655.16     .06       0
 1675.16     .05       0 1775.16     .06       0
#XS Ineff= 2 , 0
         1012.18 1967.72 1211.52         1968.09
Permanent Ineff=
       F       F
Bank Sta=1154.4,1176.3
XS Rating Curve= 0 ,0
Exp/Cntr(USF)=0,0
Exp/Cntr=0.3,0.1

Type RM Length L Ch R = 1 ,7492    ,486.5,491.8,464.2
XS GIS Cut Line= 5
2296065.11361941 679753.49552332 2295783.0390624679993.421008594
2294880.07625634680051.781261769 2294735.0049065680049.351852785
2294525.05138286680123.110460094
#Sta/Elev= 30
       0 2036.71    82.7 2030.37     131 2024.41     206 2006.83   221.8 2001.91
   258.5 1986.93     287 1978.35   305.8 1974.06   347.8 1968.68   601.7 1965.28
   649.8 1963.01   697.9 1963.46   914.3 1960.33  1037.9 1960.97  1090.7 1960.21
  1095.7 1958.54  1102.7 1956.48  1114.7 1956.63 1119.781958.557  1126.8 1960.27
  1154.8 1960.15  1198.9 1962.52    1251 1968.94  1329.4 1976.21  1359.1 1981.26
  1407.1 1982.19  1419.1 1985.14  1457.2 1988.27  1554.7 1991.32  1642.8 1991.25
#Mann= 5 ,-1,0
       0     .05       0      70      .1       0     330     .05       0
  1095.7    .045       0 1119.78     .05       0
#XS Ineff= 2 , 0
           988.7 1969.96 1148.17         1967.72
Permanent Ineff=
       F       F
Bank Sta=1095.7,1119.78
XS Rating Curve= 0 ,0
Exp/Cntr(USF)=0,0
Exp/Cntr=0.3,0.1

Type RM Length L Ch R = 1 ,7001    ,645.8,650,640.7
XS GIS Cut Line= 4
2295982.61671832679551.756376544 2295326.4353459679476.421734251
2294799.20470537679939.8158991092294521.01731152680044.488498354
#Sta/Elev= 30
       0 2038.34      59 2036.68   155.5 2031.83     200 2023.74   304.4  2000.9
   376.9  1994.5   443.4 1991.59   505.7 1987.37   529.9 1982.99   574.2 1970.34
   610.4 1963.99     708 1962.68   784.5 1959.54     801 1957.68   861.6 1958.26
   879.8 1956.63     904 1957.68   908.31956.962   920.6 1954.72   932.4 1956.49
   976.7 1957.38   994.9 1959.56  1028.3 1958.71  1192.6 1959.24  1266.3  1960.7
  1286.2 1962.23  1339.8 1971.26  1455.4 1984.32  1566.5 1991.53  1659.7 1993.43
#Mann= 7 ,-1,0
       0     .05       0      60      .1       0     510     .05       0
  800.32      .1       0  830.32     .05       0  1024.6    .045       0
  1057.4     .05       0
#XS Ineff= 2 , 0
                         1244.74         1969.96
Permanent Ineff=
       F       F
Bank Sta=908.3,932.4
XS Rating Curve= 0 ,0
Exp/Cntr(USF)=0,0
Exp/Cntr=0.3,0.1

Type RM Length L Ch R = 1 ,6351    ,502.9,522.2,518.6
XS GIS Cut Line= 4
2295237.40931857678831.6970756992295106.42778547679070.962584563
2294569.48235421679550.3095314692294454.71746772 679748.36333353
#Sta/Elev= 30
       0 2012.99    34.4  1996.4      58  1988.2    97.5 1979.62   143.1 1972.46
     175 1970.03   185.8 1970.75     226 1968.52   238.8 1968.58   247.9 1970.75
   270.7 1966.63   288.1 1965.19   516.4 1957.24   540.4  1958.1   559.2 1955.42
     619 1956.48  637.261954.223   648.5 1951.98   661.9 1954.25   667.2 1955.72
   714.6  1954.6   736.9 1955.85   750.6 1955.08   967.2 1954.91  1004.4 1959.42
  1019.1 1964.71  1051.3 1979.66  1069.8 1985.66    1093 1987.29  1221.5 1990.45
#Mann= 4 ,-1,0
       0      .1       0  637.26    .045       0   661.9      .1       0
 1062.55     .05       0
#XS Ineff= 2 , 0
           590.7 1961.54
Permanent Ineff=
       F       F
Bank Sta=637.26,661.9
XS Rating Curve= 0 ,0
Exp/Cntr(USF)=0,0
Exp/Cntr=0.3,0.1

Type RM Length L Ch R = 1 ,5828    ,59.9,53.3,52.5
XS GIS Cut Line= 4
2295151.04763012678820.6843096832294946.23385312679119.850500806
2294354.80530605679308.5553290532294435.35004982679667.554758401
#Sta/Elev= 30
       0 1996.71    10.3 1992.27    24.8 1987.72   121.8 1966.66   126.6 1966.27
   194.5 1965.03   244.1 1963.11   344.9    1962   419.4 1960.03   436.1 1960.57
   494.9 1958.78   549.9 1958.62     604 1955.03   629.2 1954.29   738.4 1954.93
   785.4 1953.81   881.2 1953.65   896.31952.004   906.3 1950.03   914.7 1949.59
   927.3 1951.95   935.7 1954.03   983.4 1956.87  1033.2 1972.01    1066 1976.84
  1099.2 1980.32  1156.8 1984.12  1242.8 1986.86  1258.7 1988.21  1351.3 1989.21
#Mann= 5 ,-1,0
       0      .1       0  592.56     .05       0  782.56      .1       0
   896.3    .045       0   927.3     .05       0
#XS Ineff= 2 , 0
          714.73 1963.15
Permanent Ineff=
       F       F
Bank Sta=896.3,927.3
XS Rating Curve= 0 ,0
Exp/Cntr(USF)=0,0
Exp/Cntr=0.3,0.1

Type RM Length L Ch R = 1 ,5775    ,89,92.6,95.1
XS GIS Cut Line= 4
2295093.51567029678786.1651337842294888.70189329679085.331324907
2294297.27334622679274.0361531552294377.81808999679633.035582503
#Sta/Elev= 30
       0 1998.35    27.9 1987.22    46.3 1982.75   139.4 1967.96   172.9 1964.99
   241.2 1962.19   357.1  1961.6   401.1 1960.04   484.9 1958.98   505.9 1958.03
   534.7 1954.45   665.7 1955.09   792.6 1953.06   819.9 1951.63     846  1949.6
   862.6 1949.91  868.881951.652   883.7 1953.71   959.3 1954.93   971.9 1957.03
   983.4 1961.18   998.9 1962.75  1018.6 1962.49  1033.2 1959.67  1068.8 1960.68
  1080.9 1963.04  1115.8 1973.11  1150.6 1978.05  1197.6 1981.11  1351.3 1988.25
#Mann= 5 ,-1,0
       0      .1       0  572.56     .05       0   819.9    .045       0
  868.88      .1       0  892.56     .05       0
#XS Ineff= 2 , 0
          644.96 1960.45
Permanent Ineff=
       F       F
Bank Sta=819.9,868.88
XS Rating Curve= 0 ,0
Exp/Cntr(USF)=0,0
Exp/Cntr=0.3,0.1

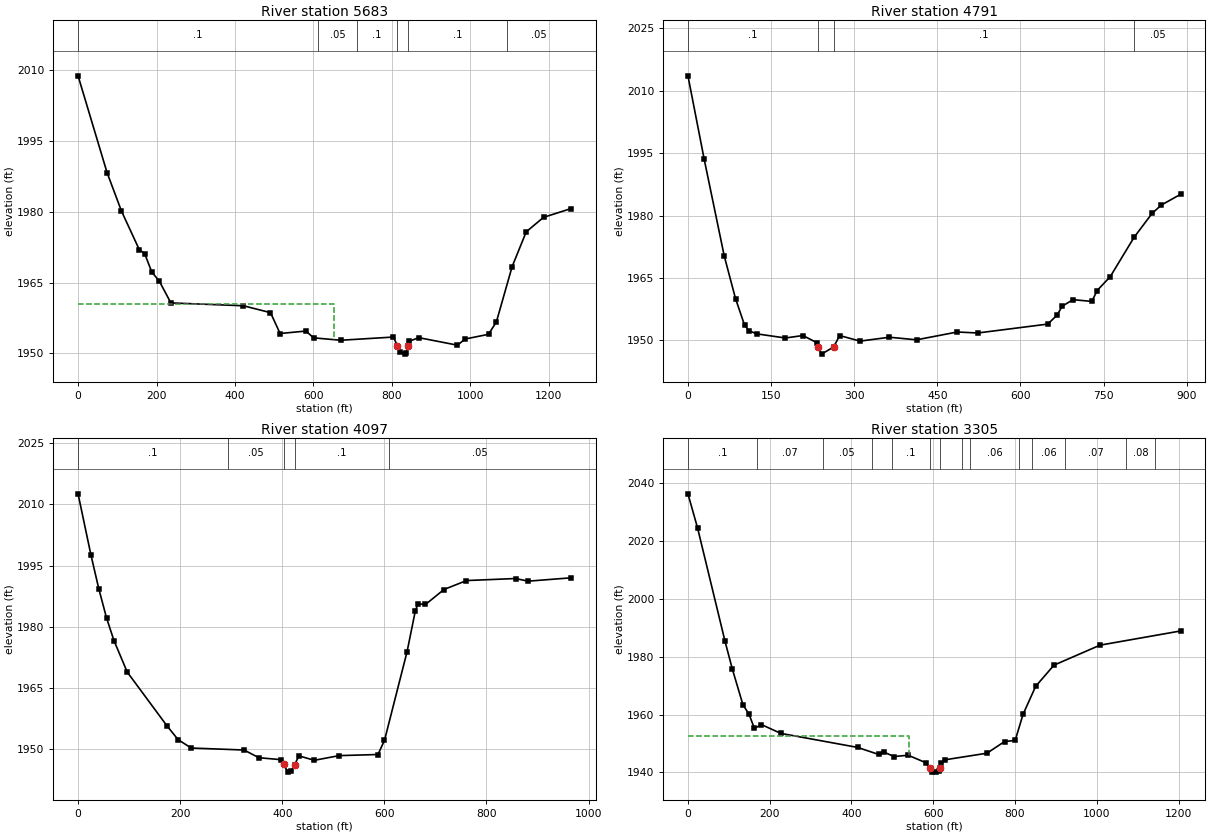
Type RM Length L Ch R = 1 ,5683    ,895.1,891.3,875.9
XS GIS Cut Line= 4
2294929.56009264678692.5837732282294861.27859642679057.627156837
2294220.48301656679178.4328809092294208.66506529679410.852589178
#Sta/Elev= 30
       0  2008.8    73.9  1988.3   110.5 1980.17     156 1971.98   169.7 1971.14
   187.8 1967.25   207.4 1965.25   236.6 1960.68   421.3 1960.08   490.5 1958.62
     515  1954.2   580.8 1954.72   600.4 1953.28   669.6 1952.77     804 1953.45
   813.7 1951.63   820.2 1950.35   832.5 1949.83   836.5 1950.05   840.11951.648
   844.8 1952.57   868.5 1953.32   966.8 1951.73   987.1 1953.04  1046.2 1954.03
  1066.3 1956.66  1106.4 1968.37  1142.4 1975.75  1186.4 1978.81  1256.2 1980.66
#Mann= 6 ,-1,0
       0      .1       0  611.37     .05       0  711.37      .1       0
   813.7    .045       0   840.1      .1       0 1093.46     .05       0
#XS Ineff= 2 , 0
          652.71 1960.45
Permanent Ineff=
       F       F
Bank Sta=813.7,840.1
XS Rating Curve= 0 ,0
Exp/Cntr(USF)=0,0
Exp/Cntr=0.3,0.1

Type RM Length L Ch R = 1 ,4791    ,687.9,694.4,683.4
XS GIS Cut Line= 3
2294174.63239173678564.985564134  2294039.382505679226.790835137
2294105.03778982679430.322218084
#Sta/Elev= 30
       0 2013.59    29.4 1993.48    65.5 1970.29    85.9 1960.02   102.3 1953.61
   110.4  1952.3   124.3 1951.56   175.8 1950.57   207.5 1951.16   232.8 1949.43
  234.96 1948.34   241.1 1946.69   263.11948.422   273.7 1951.16   310.5 1949.82
   363.6 1950.75   412.5 1950.13     486 1952.01   522.8 1951.77   649.3 1953.91
   665.7 1956.02   675.5 1958.22   694.8 1959.78   728.9 1959.36   738.4 1961.98
   762.1 1965.33   805.1 1974.78   837.7 1980.55   854.5 1982.55   889.3 1985.13
#Mann= 4 ,-1,0
       0      .1       0  234.96    .045       0   263.1      .1       0
  805.48     .05       0
Bank Sta=234.96,263.1
XS Rating Curve= 0 ,0
Exp/Cntr(USF)=0,0
Exp/Cntr=0.3,0.1

Type RM Length L Ch R = 1 ,4097    ,773.5,791.4,797.5
XS GIS Cut Line= 4
2293748.45956839678484.3048021172293665.78254306678682.081215654
2293806.81982157679040.3483254232293776.95255437679405.057656401
#Sta/Elev= 30
       0 2012.61    25.3 1997.57    40.6 1989.33    55.9 1982.12    70.3 1976.63
    96.3  1968.9   174.4 1955.67     196 1952.32   221.7 1950.27   325.2 1949.78
   354.3 1947.89   397.5 1947.42   402.5 1946.26   411.1 1944.36   417.5 1944.67
     424 1946.13   432.6 1948.35   462.7 1947.26   511.6 1948.41   587.4 1948.68
   600.2 1952.14   644.4 1973.88   660.4 1983.78   665.7 1985.63   680.5 1985.47
   716.6 1989.14   760.8 1991.34   857.1 1991.84   881.5 1991.19   965.3 1992.01
#Mann= 5 ,-1,0
       0      .1       0  294.36     .05       0   402.5    .045       0
     424      .1       0  609.39     .05       0
Bank Sta=402.5,424
XS Rating Curve= 0 ,0
Exp/Cntr(USF)=0,0
Exp/Cntr=0.3,0.1

Type RM Length L Ch R = 1 ,3305    ,387.5,383.3,376.5
XS GIS Cut Line= 4
 2293605.0983111678361.4010021192293444.94985092678442.817157783
  2293072.651063678954.5501184932292902.72185668679308.962569564
#Sta/Elev= 30
       0 2036.39    23.5  2024.6    90.8 1985.29   108.7  1975.7   134.4 1963.44
   149.6 1960.04   162.6 1955.19   179.7 1956.53   227.1 1953.48   415.1 1948.62
   466.5 1946.19   479.4 1947.01   504.1 1945.46   538.7 1945.92   582.1 1943.31
   591.4 1941.55   597.1 1940.23   605.7 1940.07   612.9 1940.48   615.41941.609
     620 1943.21   629.7 1944.36   731.5 1946.62   774.6 1950.67   800.4 1951.04
   819.8 1960.11   850.6 1969.77   895.3 1977.09  1007.9 1984.01  1205.5 1988.94
#Mann= 14 ,-1,0
       0      .1       0     170     .07       0  329.66     .05       0
  449.66     .07       0  499.66      .1       0   591.4    .045       0
   615.4      .1       0  669.66     .07       0  689.66     .06       0
  809.66      .1       0  842.49     .06       0  922.49     .07       0
 1072.49     .08       0 1142.49     .07       0
#XS Ineff= 2 , 0
          540.62 1952.53
Permanent Ineff=
       F       F
Bank Sta=591.4,615.4
XS Rating Curve= 0 ,0
Exp/Cntr(USF)=0,0
Exp/Cntr=0.3,0.1