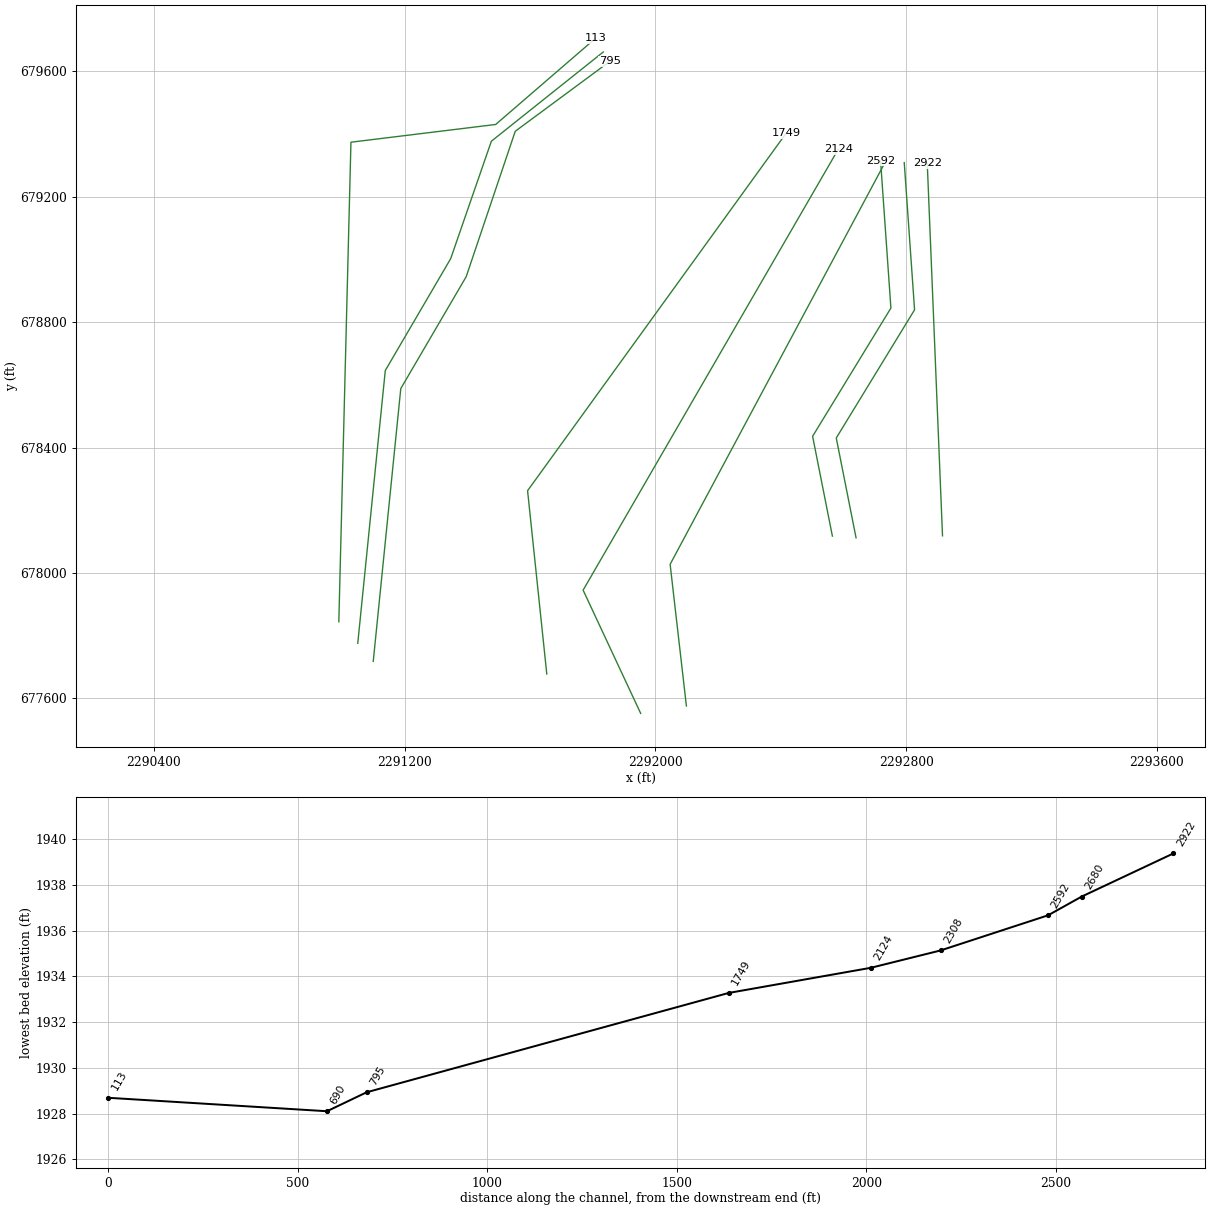
HEC-RAS study KINGSRN.prj: KINGSRN

--- KINGSRN.g01 (geometry) --- (continued)

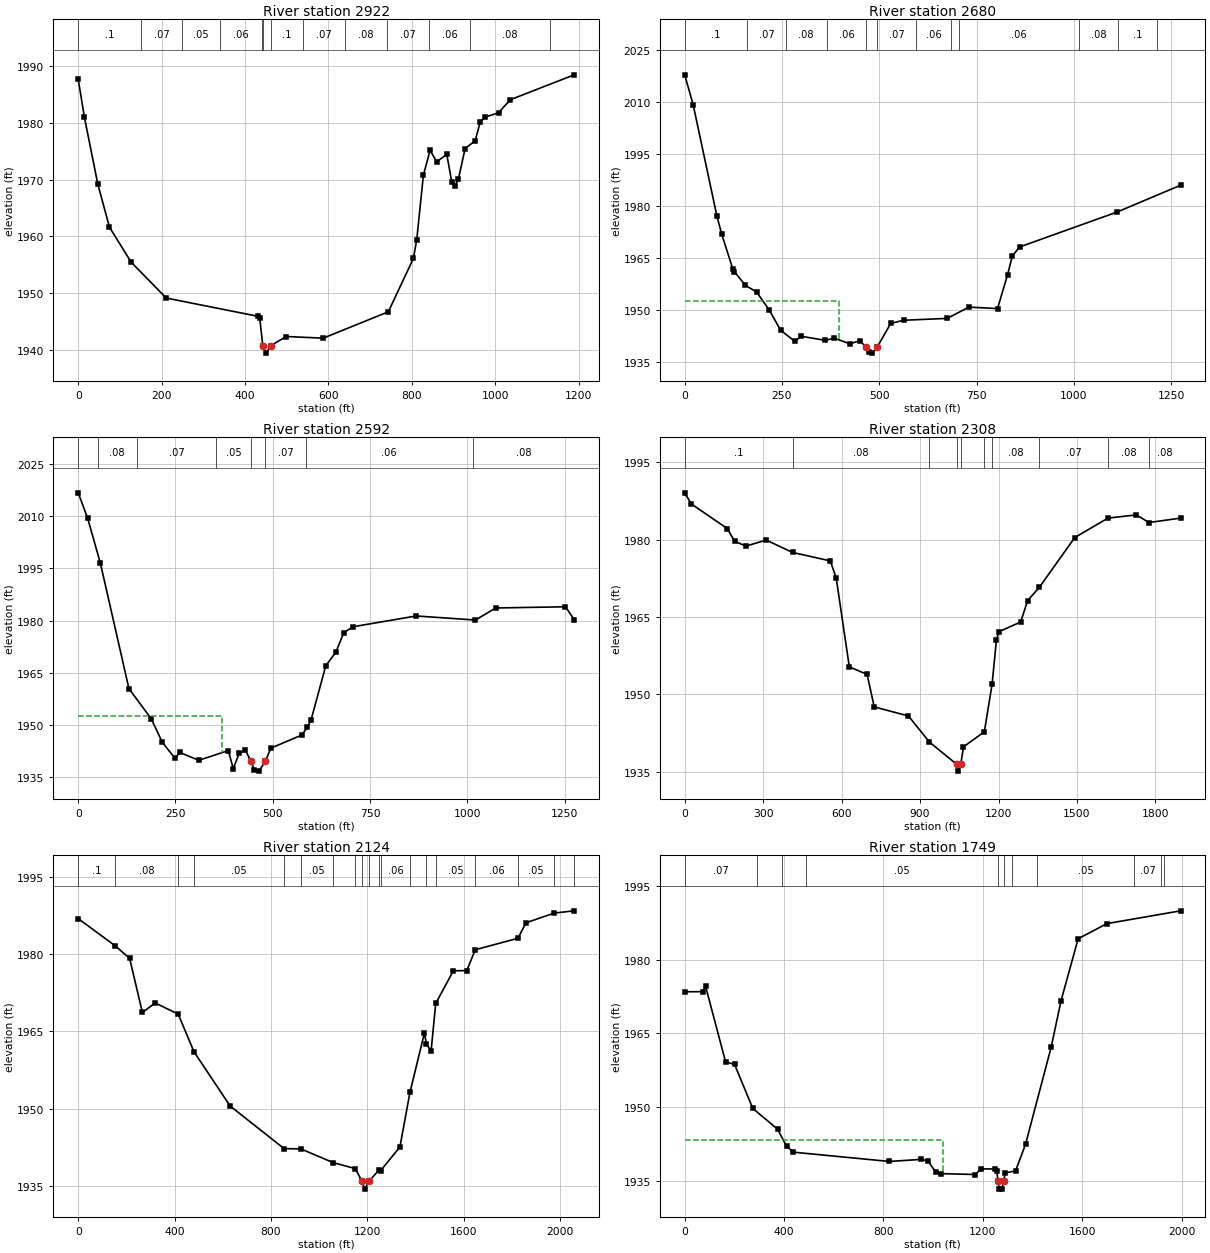
Type RM Length L Ch R = 1 ,2922    ,249.3,241.9,233.3
XS GIS Cut Line= 2
2292916.18456462678118.2591294972292867.54390429679306.321690277
#Sta/Elev= 30
       0 1987.68    14.9 1980.99      47  1969.2      75  1961.6     127 1955.43
   211.1 1949.11   431.3 1945.88   435.3  1945.5  442.711940.612   451.3 1939.39
  461.441940.702   498.9 1942.32   587.4 1942.03   743.5 1946.68   803.6 1956.09
   811.6 1959.34   827.6 1970.77   843.6 1975.16   859.6 1973.16   883.7 1974.45
   895.7 1969.58   903.7 1968.88   911.7 1970.16   927.7 1975.49   951.7 1976.84
   963.7 1980.13   975.8 1981.04  1007.8 1981.79  1035.8 1984.09  1189.1 1988.49
#Mann= 13 ,-1,0
       0      .1       0     150     .07       0     250     .05       0
     340     .06       0     440      .1       0  442.71    .045       0
  461.44      .1       0     540     .07       0     640     .08       0
     740     .07       0     840     .06       0     940     .08       0
    1130     .07       0
Bank Sta=442.71,461.44
XS Rating Curve= 0 ,0
Exp/Cntr(USF)=0,0
Exp/Cntr=0.3,0.1

Type RM Length L Ch R = 1 ,2680    ,88.1,88.6,83
XS GIS Cut Line= 4
2292640.36808535678111.8198376042292577.22439569678430.283663706
2292827.05377651678839.3449575792292794.10924278679308.804563298
#Sta/Elev= 30
       0 2017.94    21.8 2009.29    82.9 1977.08    95.2 1971.88   123.7 1961.81
   127.8 1961.03   156.3 1957.07   184.9 1955.15   217.5 1949.94   246.3 1944.17
   282.8 1940.91   299.1 1942.37   360.9 1941.21   384.3 1941.82   424.9  1940.2
   449.9 1941.08  466.331939.253   473.4 1937.94   482.7  1937.5   494.8 1939.24
   529.6 1946.09   562.4    1947   674.9 1947.54   730.5 1950.81     804 1950.37
   829.9 1960.15   842.1 1965.58   860.9 1968.19  1110.6 1978.25  1274.6 1986.03
#Mann= 12 ,-1,0
       0      .1       0     160     .07       0     260     .08       0
  364.66     .06       0  466.33    .045       0   494.8     .07       0
  594.66     .06       0  684.66     .07       0  704.66     .06       0
 1013.98     .08       0 1113.98      .1       0 1213.98     .08       0
#XS Ineff= 2 , 0
           396.9 1952.58
Permanent Ineff=
       F       F
Bank Sta=466.33,494.8
XS Rating Curve= 0 ,0
Exp/Cntr(USF)=0,0
Exp/Cntr=0.3,0.1

Type RM Length L Ch R = 1 ,2592    ,278.9,283.6,290.8
XS GIS Cut Line= 4
2292564.87019554678117.3105932272292501.72650588678435.774419329
 2292751.5558867678844.8357132012292718.61135297 679314.29531892
#Sta/Elev= 30
       0 2016.73    24.3  2009.4      57 1996.48   130.4 1960.39   187.4 1951.79
     216 1945.01   248.9 1940.33   260.8 1942.06   309.8 1939.79   385.7 1942.59
   398.4 1937.43   413.8 1941.82   429.4 1942.64   444.5 1939.52   452.9 1936.91
   464.2 1936.68     481 1939.48     495 1943.29   574.4 1947.04   588.8 1949.26
   598.2 1951.31   636.3 1967.01   662.1 1970.87   682.5 1976.51     706  1978.2
   868.5 1981.31  1020.9 1980.14    1073 1983.61  1252.3 1983.95  1274.6 1980.28
#Mann= 8 ,-1,0
       0      .1       0      50     .08       0     150     .07       0
  354.66     .05       0   444.5    .045       0     481     .07       0
  584.66     .06       0 1013.98     .08       0
#XS Ineff= 2 , 0
          370.54 1952.58
Permanent Ineff=
       F       F
Bank Sta=444.5,481
XS Rating Curve= 0 ,0
Exp/Cntr(USF)=0,0
Exp/Cntr=0.3,0.1

Type RM Length L Ch R = 1 ,2308    ,186.8,184,182.6
XS GIS Cut Line= 3
2292099.09854734677575.3242065742292047.16774327 678027.30167345
2292726.87494018679298.262312503
#Sta/Elev= 30
       0 1989.09    25.6 1986.93   162.9 1982.16   191.1 1979.66   235.4 1978.78
   311.9 1979.93   412.4 1977.53   556.9  1975.9   579.6 1972.52   629.5 1955.35
   697.5  1953.9   724.7 1947.59   855.7 1945.83   935.9 1940.77  1039.3 1936.49
  1046.8 1935.14  1055.8 1936.53  1065.9 1939.84  1145.7 1942.77  1175.3 1951.96
  1191.9 1960.52    1201 1962.16  1284.6 1964.05  1311.2  1968.2  1356.2 1970.78
  1491.3 1980.41  1618.3 1984.19  1727.2 1984.81  1775.2 1983.33  1896.2 1984.19
#Mann= 10 ,-1,0
       0      .1       0   412.4     .08       0   935.9     .07       0
  1039.3    .045       0  1055.8     .08       0  1145.7     .07       0
  1175.3     .08       0  1356.2     .07       0  1618.3     .08       0
  1775.2     .08       0
Bank Sta=1039.3,1055.8
XS Rating Curve= 0 ,0
Exp/Cntr(USF)=0,0
Exp/Cntr=0.3,0.1

Type RM Length L Ch R = 1 ,2124    ,373,374.5,363.2
XS GIS Cut Line= 3
2291953.20917046677551.7627641142291769.57954236677944.940339114
2292583.31913443679351.138289147
#Sta/Elev= 30
       0 1986.91   153.7 1981.62   213.5 1979.18   266.4 1968.68   319.4 1970.53
     415 1968.37   480.4 1961.07   630.8 1950.51   854.8 1942.24   924.1 1942.19
  1059.6 1939.51  1149.9 1938.37 1176.581936.037  1188.4 1934.38 1208.811935.999
  1247.6 1938.05  1255.7 1937.99  1335.4 1942.57    1377 1953.16  1437.1  1964.7
  1445.4 1962.52  1464.8 1961.23    1484 1970.43  1557.2 1976.78  1612.8 1976.81
    1648 1980.86  1825.3 1983.09  1858.7  1986.1  1975.8 1987.98  2058.6 1988.42
#Mann= 19 ,-1,0
       0      .1       0   153.7     .08       0     415     .06       0
   480.4     .05       0   854.8     .07       0   924.1     .05       0
  1059.6     .07       0  1149.9     .05       0 1176.58    .045       0
 1208.81     .05       0  1247.6     .07       0  1255.7     .06       0
    1377     .05       0  1445.4     .07       0    1484     .05       0
    1648     .06       0  1825.3     .05       0  1975.8     .07       0
  2058.6     .06       0
Bank Sta=1176.58,1208.81
XS Rating Curve= 0 ,0
Exp/Cntr(USF)=0,0
Exp/Cntr=0.3,0.1

Type RM Length L Ch R = 1 ,1749    ,955.6,954.6,947.4
XS GIS Cut Line= 3
2291653.66359033677677.5202041682291592.39794246678262.156204586
2292417.78946703 679403.43227281
#Sta/Elev= 30
       0  1973.5    72.1 1973.53    84.1 1974.62   164.6 1959.22   200.8  1958.7
   274.1 1949.73   373.7 1945.51   409.9 1942.04     438 1940.81   823.6 1938.92
   951.9 1939.34   979.4 1939.04  1010.6 1936.75  1030.4 1936.44  1169.1 1936.26
  1193.8 1937.41  1248.1 1937.38  1256.4    1937 1260.94 1934.93  1265.9  1933.4
  1276.9 1933.28  1283.7 1934.99  1290.5 1936.57  1331.8    1937  1371.9 1942.39
  1475.2 1962.21  1515.1 1971.69  1583.8 1984.31    1700  1987.4  1996.3    1990
#Mann= 11 ,-1,0
       0     .07       0     290     .08       0     390     .06       0
     490     .05       0 1260.94    .045       0  1283.7     .05       0
 1317.84      .1       0 1417.84     .05       0 1807.84     .07       0
 1917.84     .06       0 1927.84     .08       0
#XS Ineff= 2 , 0
         1040.97 1943.37
Permanent Ineff=
       F       F
Bank Sta=1260.94,1283.7
XS Rating Curve= 0 ,0
Exp/Cntr(USF)=0,0
Exp/Cntr=0.3,0.1

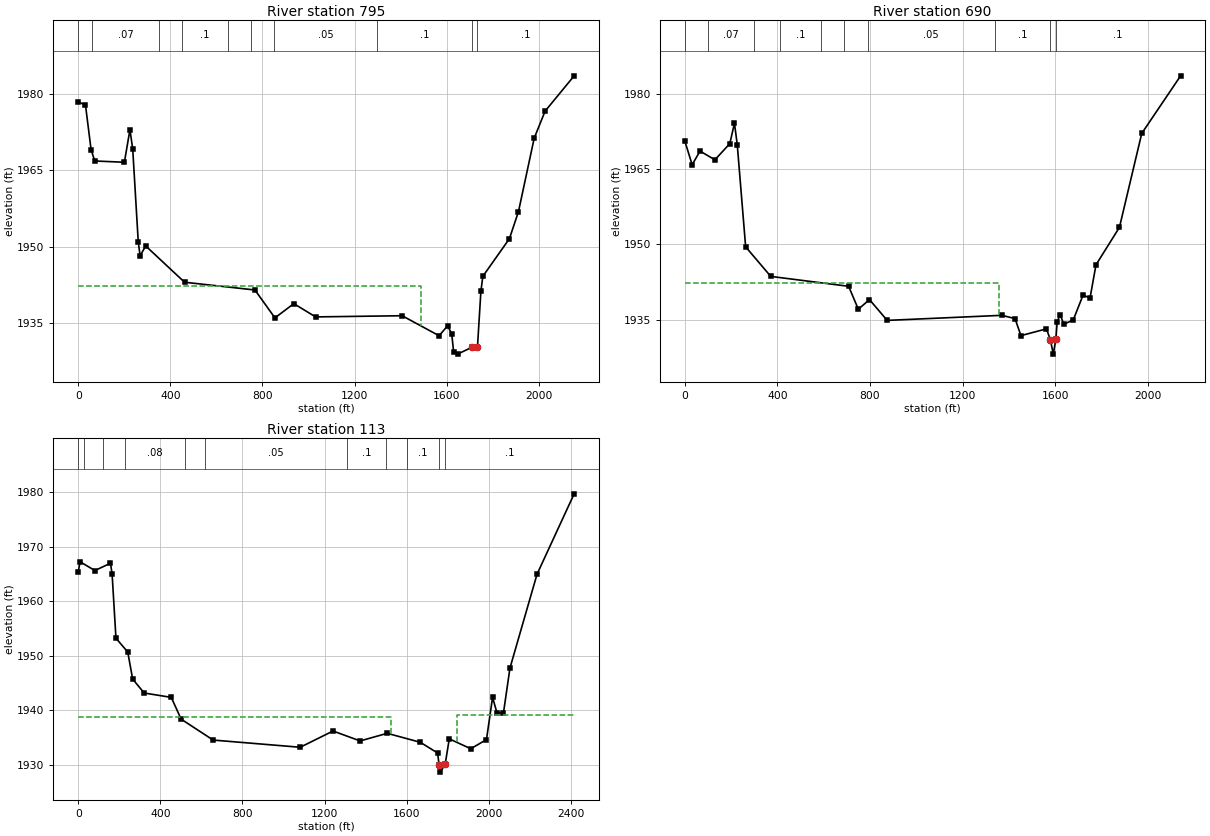
Type RM Length L Ch R = 1 ,795     ,113.3,104.5,113.2
XS GIS Cut Line= 5
2291100.00811764677717.696446055 2291187.8602076678587.981212213
2291396.50892126678944.880327672 2291552.9954565 679408.84917777
2291855.26155351679632.213116491
#Sta/Elev= 30
       0 1978.41    31.6 1977.77    55.8 1969.06    71.8 1966.81   200.5 1966.56
   224.6 1972.95   236.7 1969.15   260.8 1950.88   268.8 1948.21     293 1950.15
   461.8 1943.03   767.4 1941.51   854.2 1936.04   936.3 1938.83  1030.8 1936.23
  1406.6 1936.46    1567 1932.54  1603.8 1934.47  1621.9 1932.93  1630.4 1929.29
  1647.3 1928.93  1709.5 1930.27 1733.711930.285  1748.6 1941.24    1757 1944.18
  1872.6 1951.58  1911.8 1956.88  1980.2  1971.3  2027.4 1976.58  2153.6 1983.51
#Mann= 10 ,-1,0
       0     .06       0      60     .07       0     350     .08       0
     450      .1       0     650     .08       0     750     .07       0
     850     .05       0 1298.12      .1       0  1709.5    .045       0
 1733.71      .1       0
#XS Ineff= 2 , 0
         1486.71 1942.28
Permanent Ineff=
       F       F
Bank Sta=1709.5,1733.71
XS Rating Curve= 0 ,0
Exp/Cntr(USF)=0,0
Exp/Cntr=0.3,0.1

Type RM Length L Ch R = 1 ,690     ,586.5,577.7,560.8
XS GIS Cut Line= 5
2291050.59131704 677775.34938009  2291138.443407678645.634146249
2291347.09212065679002.5332617082291476.83867601679377.175753962
2291833.86407885679661.846724585
#Sta/Elev= 30
       0 1970.69    32.3 1965.87    66.2  1968.6   130.5 1966.86   194.8 1970.08
   214.9 1974.16     227 1969.88   263.2  1949.5   371.7  1943.6   707.9 1941.63
   749.6 1937.06   797.9 1938.97   874.3 1934.83  1369.7 1935.84  1426.3 1935.18
  1451.8 1931.79  1561.8 1933.14  1578.8 1930.98  1591.5  1928.1 1602.361931.031
  1608.4 1934.57  1621.1 1935.99  1636.9 1934.05  1677.8 1934.93  1719.6 1939.83
  1750.3 1939.34  1775.8 1945.91  1877.1 1953.39  1973.3 1972.12  2141.2 1983.61
#Mann= 10 ,-1,0
       0     .08       0     100     .07       0     300     .08       0
     410      .1       0     590     .08       0     690     .07       0
     790     .05       0 1338.12      .1       0  1578.8    .045       0
 1602.36      .1       0
#XS Ineff= 2 , 0
         1356.59 1942.28
Permanent Ineff=
       F       F
Bank Sta=1578.8,1602.36
XS Rating Curve= 0 ,0
Exp/Cntr(USF)=0,0
Exp/Cntr=0.3,0.1

Type RM Length L Ch R = 1 ,113     ,,,
XS GIS Cut Line= 4
2290990.19300519677843.9838253712291028.85890629679374.024060234
 2291490.6580077679430.5881944522291809.06782646 679705.40214356
#Sta/Elev= 30
       0 1965.43     9.2 1967.27    81.3 1965.66   157.2    1967   165.2 1964.99
   183.9 1953.25   241.3 1950.72   265.3 1945.76   321.3  1943.2   453.3  1942.4
   501.4 1938.41   657.4 1934.57  1081.5 1933.25  1241.6 1936.23  1373.6 1934.41
  1505.7 1935.81  1666.9 1934.16  1751.1  1932.2 1758.081930.078  1763.6 1928.69
  1787.8  1930.1  1807.9 1934.79  1912.7 1932.98  1989.2 1934.66  2018.9  1942.4
  2040.1 1939.59  2071.8 1939.51  2103.6 1947.77  2235.6 1964.99  2416.4 1979.73
#Mann= 11 ,-1,0
       0     .07       0      30     .08       0     120     .07       0
     230     .08       0     520     .06       0     620     .05       0
    1310      .1       0    1500    .025       0 1600.53      .1       0
 1758.08    .045       0  1787.8      .1       0
#XS Ineff= 2 , 0
          1525.5 1938.88 1843.85          1939.1
Permanent Ineff=
       F       F
Bank Sta=1758.08,1787.8
XS Rating Curve= 0 ,0
Exp/Cntr(USF)=0,0
Exp/Cntr=0.3,0.1
LCMann Table=0

Chan Stop Cuts=-1
Use User Specified Reach Order=0
Composite Channel Slope=5