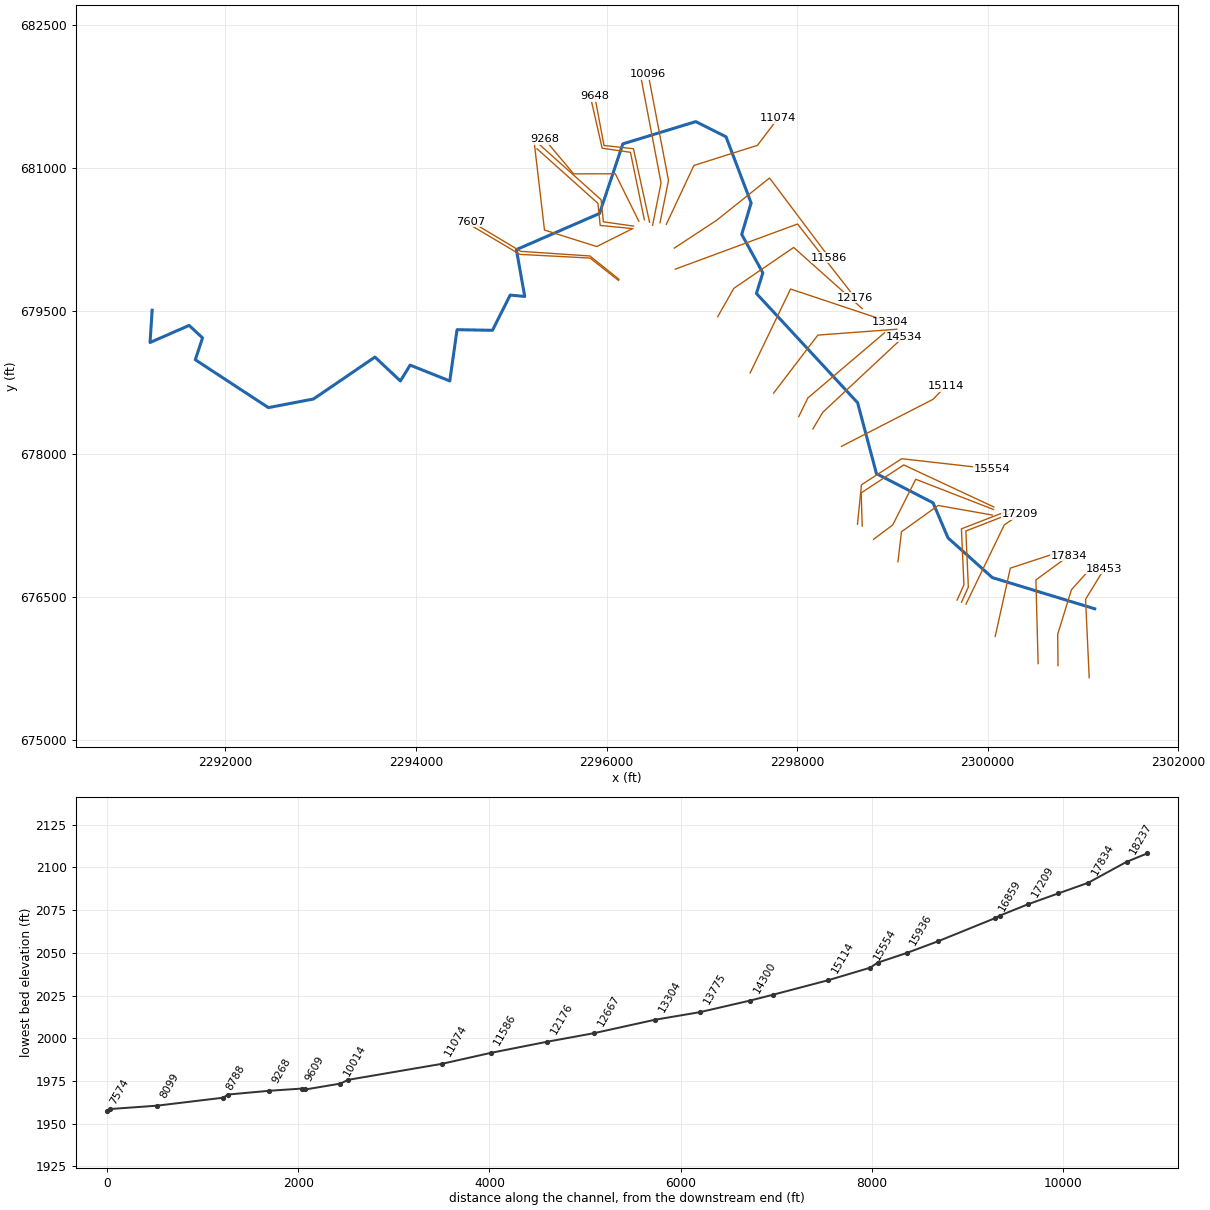
--- KINGSRN.prj (project) ---

Proj Title=KINGSRN
Current Plan=p01
Default Exp/Contr=0,0
English Units
Geom File=g01
Flow File=f01
Plan File=p01
BEGIN DESCRIPTION:
----------MODEL BY WOOD PLC 2022----------
AFH study
Randolph County, WV
HEC-RAS Version: RAS 6.2
Vertical Datum: NAVD88
Projection: NAD 1983 StatePlane West Virginia S FIPS 4702 (US Feet)
Terrain: 1-meter LIDAR (FEMA Region III 3DEP collected 2016-2018)
Land Use: 2019 NLCD
Hydrologic Method:
WV SIR2010-5033 regression equations
Additional Model Notes:
None
END DESCRIPTION:
DSS Export Rating Curves= 0
DSS Export Rating Curve Sorted= 0
DSS Export Volume Flow Curves= 0
DXF OffsetX= 0
DXF OffsetY= 0
DXF ScaleX= 0
DXF ScaleY= 0

--- KINGSRN.p01 (plan) ---

Plan Title=Floodplain
Program Version=4.00
Geom File=g01
Flow File=f01
K Sum by GR=0
Std Step Tol=0.01
Critical Tol=0.01
Num of Std Step Trials=20
Max Error Tol=0.3
Flow Tol Ratio=0.001
Split Flow NTrial=30
Split Flow Tol=0.02
Split Flow Ratio=0.02
Log Output Level=0
Friction Slope Method=1
Unsteady Friction Slope Method=2
Unsteady Bridges Friction Slope Method=1
Global Log Level=0
CheckData=False
Run HTab=0
Run UNet=0
Run PostProcess=0
UNET Theta=0
UNET Theta Warmup=0
UNET ZTol=0
UNET ZSATol=0
UNET MxIter=0
UNET MaxInSteps=0
UNET DtIC=0
UNET DtMin=0
UNET MaxCRTS=0
UNET WFStab=0
UNET SFStab=0
UNET WFX=0
UNET SFX=0
UNET DSS MLevel=0
UNET DZMax Abort=0
UNET Convert EG Bridges=0
UNET Use Existing IB Tables=0
UNET Froude Limit=0
UNET Froude Power=0
Write IC File=0
Echo Input=False
Echo Output=False
Write Detailed=0

--- KINGSRN.f01 (steady flow) ---

Flow Title=Flow
Program Version=6.20
Number of Profiles= 1
Profile Names=P100yr
River Rch & RM=KINGSRN,Main,18453
     339
River Rch & RM=KINGSRN,Main,14534
     552
River Rch & RM=KINGSRN,Main,11074
     704
River Rch & RM=KINGSRN,Main,10096
     903
River Rch & RM=KINGSRN,Main,6351
    1060
Boundary for River Rch & Prof#=KINGSRN,Main            , 1
Up Type= 0
Dn Type= 3
Dn Slope=0.0015
DSS Import GetInterval= 0
DSS Import GetPeak= 0
DSS Import FillOption= 0

--- KINGSRN.g01 (geometry) ---

Geom Title=Geometry
Program Version=6.20

River Reach=KINGSRN         ,Main
Reach XY= 30
      2301123.04      676375.429     2300047.736       676703.12
     2299583.414      677119.396     2299426.208      677487.452
     2298832.459      677793.441     2298634.716      678537.365
     2297572.656      679684.068     2297640.063      679900.214
     2297418.676      680303.593      2297517.03      680634.306
     2297253.583      681328.463     2296936.536      681487.467
     2296170.666      681253.927     2295926.357      680523.877
     2295053.797      680144.241     2295141.195      679652.972
      2294988.65      679667.338     2294802.835      679297.582
      2294431.08      679304.203      2294354.73      678766.261
     2293938.436      678932.315     2293836.455      678765.942
     2293569.485      679016.792     2292925.118      678577.059
     2292451.194      678486.186      2291684.14      678988.741
     2291759.933      679218.097       2291619.2      679349.084
     2291209.017      679169.433     2291231.387      679508.383

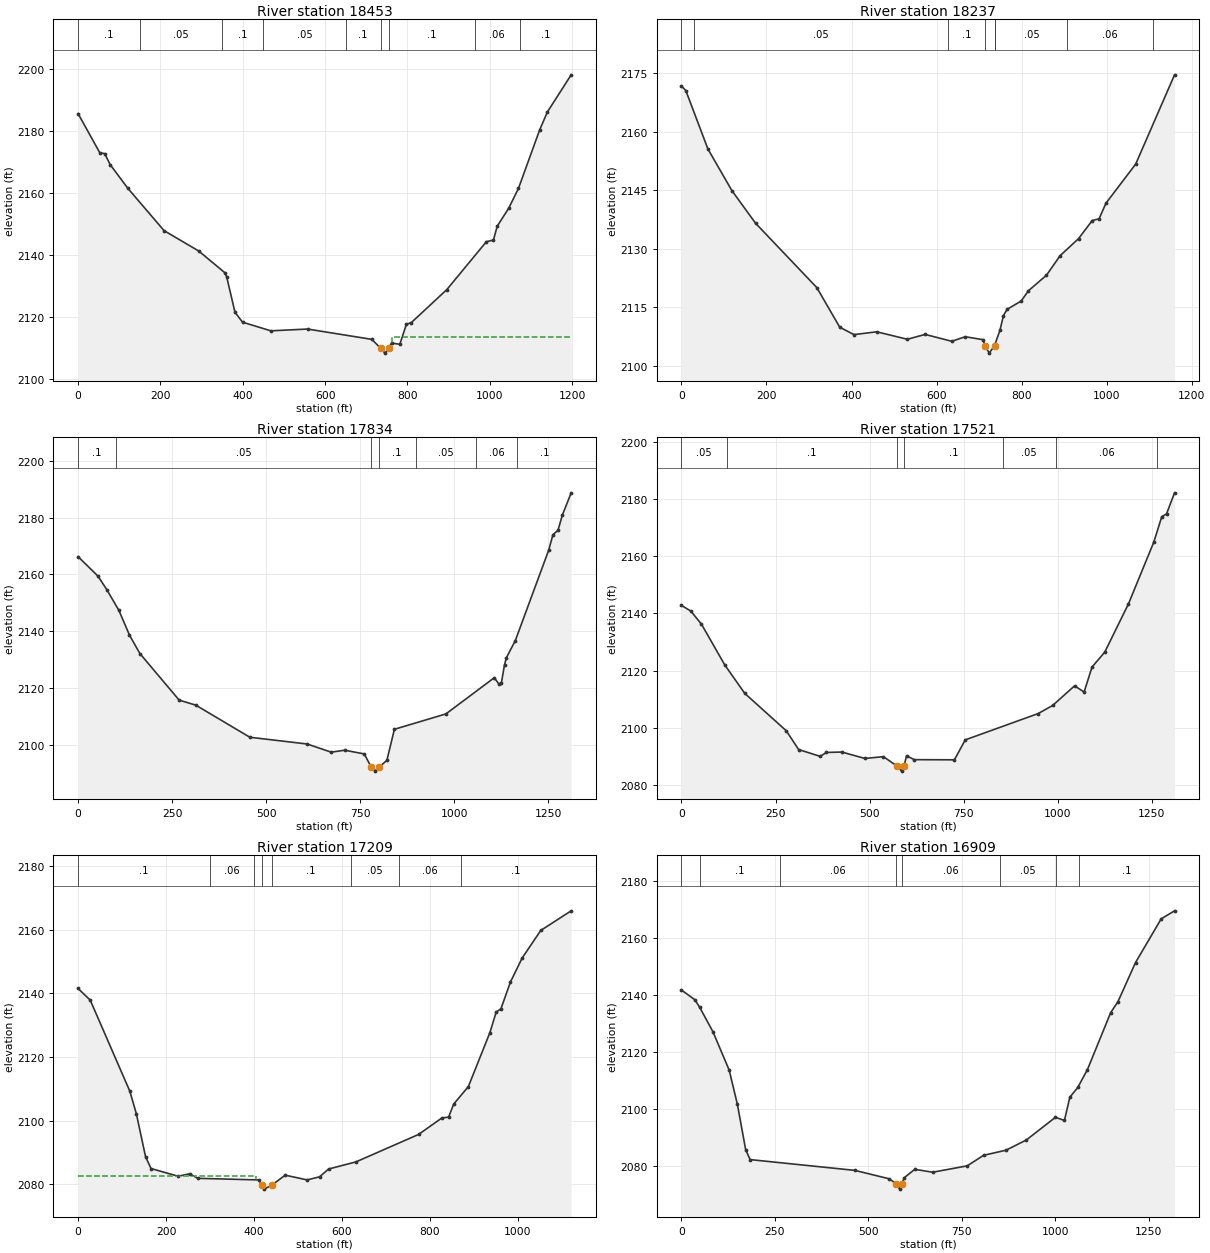
Type RM Length L Ch R = 1 ,18453   ,215.7,215.5,209.8
XS GIS Cut Line= 3
2301065.15798162675652.4995267842301026.80085866676474.827827426
 2301222.3077068676794.350213556
#Sta/Elev= 30
       0 2185.46    52.7 2172.85    64.7 2172.54    78.1 2168.98   120.8 2161.38
   208.9 2147.71     293 2141.15   357.1 2134.08   361.1 2132.77   381.1  2121.4
   399.5 2118.19   468.3  2115.4   557.3 2115.98   713.5 2112.65   734.7 2109.82
   745.5 2108.21   754.72109.827   761.5 2111.46   781.5 2111.06   797.5 2117.49
   809.6 2118.07   895.8 2128.71   991.8 2144.15  1008.9 2144.67  1018.2 2149.15
  1046.4 2155.03  1069.8 2161.35  1121.4 2180.25  1140.1    2186  1197.8 2197.96
#Mann= 9 ,-1,0
       0      .1       0     150     .05       0     350      .1       0
     450     .05       0     650      .1       0   734.7    .045       0
   754.7      .1       0  963.22     .06       0 1073.22      .1       0
#XS Ineff= 2 , 0
                          761.81         2113.29
Permanent Ineff=
       F       F
Bank Sta=734.7,754.7
XS Rating Curve= 0 ,0
Exp/Cntr(USF)=0,0
Exp/Cntr=0.3,0.1

Type RM Length L Ch R = 1 ,18237   ,397.6,403.5,404.8
XS GIS Cut Line= 4
 2300737.8800981 675778.908987562300734.27761333676106.735101071
2300878.37700389676575.0581203732301107.13478639676829.033296225
#Sta/Elev= 30
       0 2171.67    10.3 2170.51    62.3 2155.54   118.7 2144.89   174.3 2136.54
   318.3 2120.07   372.3 2109.92   405.7 2108.02   459.3 2108.74   531.3 2106.83
   573.1 2108.07   635.9 2106.31   667.4 2107.48     709 2106.73  713.852105.231
   723.8 2103.28   736.4 2105.23   748.9 2109.08   757.3 2112.89   765.6 2114.47
   799.1 2116.63   815.9 2119.24   858.4 2123.22   890.7 2128.25   933.9  2132.6
     966 2137.22   982.1 2137.66   998.3 2141.66  1068.3 2151.69  1159.6 2174.53
#Mann= 8 ,-1,0
       0      .1       0      30     .05       0  627.85      .1       0
  713.85    .045       0   736.4      .1       0  737.85     .05       0
  907.84     .06       0 1107.84      .1       0
Bank Sta=713.85,736.4
XS Rating Curve= 0 ,0
Exp/Cntr(USF)=0,0
Exp/Cntr=0.3,0.1

Type RM Length L Ch R = 1 ,17834   ,315.4,312.3,310.7
XS GIS Cut Line= 3
2300529.00269447675800.5016585832300505.58654351676678.121799708
 2300855.0275656676933.898217942
#Sta/Elev= 30
       0 2166.26    52.7 2159.46    76.7 2154.62   108.7 2147.36   136.7 2138.71
   164.3 2132.26   268.8 2115.89   312.8 2114.15   456.8 2102.86   608.9  2100.5
   672.9 2097.63   708.9 2098.31   760.9 2097.01  779.852092.257   789.2 2090.97
  799.192092.257     821 2094.74     841 2105.66   977.9 2111.05  1106.6 2123.76
  1119.5 2121.42  1125.3 2121.83  1133.9  2128.4  1138.9 2130.81  1162.5 2136.81
  1251.2 2168.54  1262.6 2173.99  1275.9 2175.51  1287.6 2180.87    1311 2188.67
#Mann= 7 ,-1,0
       0      .1       0     100     .05       0  779.85    .045       0
  799.19      .1       0  897.93     .05       0 1057.93     .06       0
 1167.93      .1       0
Bank Sta=779.85,799.19
XS Rating Curve= 0 ,0
Exp/Cntr(USF)=0,0
Exp/Cntr=0.3,0.1

Type RM Length L Ch R = 1 ,17521   ,313.5,312.5,309.2
XS GIS Cut Line= 3
2300078.65207138676085.152807577 2300237.2834852676802.067289389
2300784.41085871676981.525067901
#Sta/Elev= 30
       0 2142.84    24.8 2140.87    53.3 2136.25   114.7 2122.08     168 2112.05
   278.6  2098.9   311.4 2092.33   368.7 2089.94   385.1 2091.31   426.1 2091.46
   487.5 2089.21   536.7 2089.84   571.6 2086.65     585 2084.77  591.552086.676
   598.2 2090.16   618.5 2088.79   725.2 2088.73   754.1 2095.72   947.8 2104.94
   986.3 2107.78  1044.6 2114.66  1069.9 2112.48  1090.8 2121.23  1124.6 2126.45
  1187.7 2143.37  1255.1 2165.05  1276.1 2173.91  1288.8 2174.89  1310.1 2182.28
#Mann= 7 ,-1,0
       0     .05       0     120      .1       0   571.6    .045       0
  591.55      .1       0  854.25     .05       0  994.25     .06       0
 1264.25      .1       0
Bank Sta=571.6,591.55
XS Rating Curve= 0 ,0
Exp/Cntr(USF)=0,0
Exp/Cntr=0.3,0.1

Type RM Length L Ch R = 1 ,17209   ,297.2,299.9,301.4
XS GIS Cut Line= 3
2299771.97476719676424.3378668742300174.19219108677256.331723088
2300337.56487512677366.387632624
#Sta/Elev= 30
       0 2141.54    27.6 2137.88   117.6 2109.29   132.6 2102.13   153.5 2088.64
   165.9 2084.97   227.5 2082.55   254.2 2083.32     272 2081.89   411.1 2081.39
  418.522079.685   423.1  2078.5     440 2079.72     471 2082.88   520.8  2081.4
   548.9 2082.36   569.6 2084.82   631.8 2087.06     774 2095.67   827.3 2100.87
   842.4 2101.12     854 2105.22   887.3 2110.71   936.2 2127.63   950.6 2134.12
   961.4 2135.14   982.9 2143.54  1009.7 2151.12  1051.9 2159.77  1121.1 2165.93
#Mann= 8 ,-1,0
       0      .1       0     300     .06       0     400      .1       0
  418.52    .045       0     440      .1       0     620     .05       0
     730     .06       0     870      .1       0
#XS Ineff= 2 , 0
          405.33 2082.65
Permanent Ineff=
       F       F
Bank Sta=418.52,440
XS Rating Curve= 0 ,0
Exp/Cntr(USF)=0,0
Exp/Cntr=0.3,0.1

Type RM Length L Ch R = 1 ,16909   ,47.7,49.9,51.1
XS GIS Cut Line= 4
2299725.35342009676444.6208005042299796.68261842676603.490378591
2299770.74472812677191.9562647682300289.50253411677392.974914591
#Sta/Elev= 30
       0 2141.81    36.2 2138.36    48.8 2135.73    84.3 2127.13   127.8 2113.62
   149.7 2101.59     172 2085.57   183.8 2082.13   463.9 2078.34   556.2 2075.37
  573.882073.683   584.2 2071.74  589.852073.597   596.2 2075.74   624.3 2078.71
   672.3 2077.69   764.7 2079.93   808.5 2083.64   868.6 2085.44   922.9 2089.03
  1000.7    2097  1024.9 2095.92  1039.3 2104.07  1060.7 2107.54  1086.5 2113.82
  1148.6 2133.84    1168 2137.68  1215.1 2151.47  1283.8 2166.85  1319.5 2169.67
#Mann= 8 ,-1,0
       0     .05       0      50      .1       0  264.15     .06       0
  573.88    .045       0  589.85     .06       0  853.18     .05       0
 1003.18     .06       0 1063.18      .1       0
Bank Sta=573.88,589.85
XS Rating Curve= 0 ,0
Exp/Cntr(USF)=0,0
Exp/Cntr=0.3,0.1

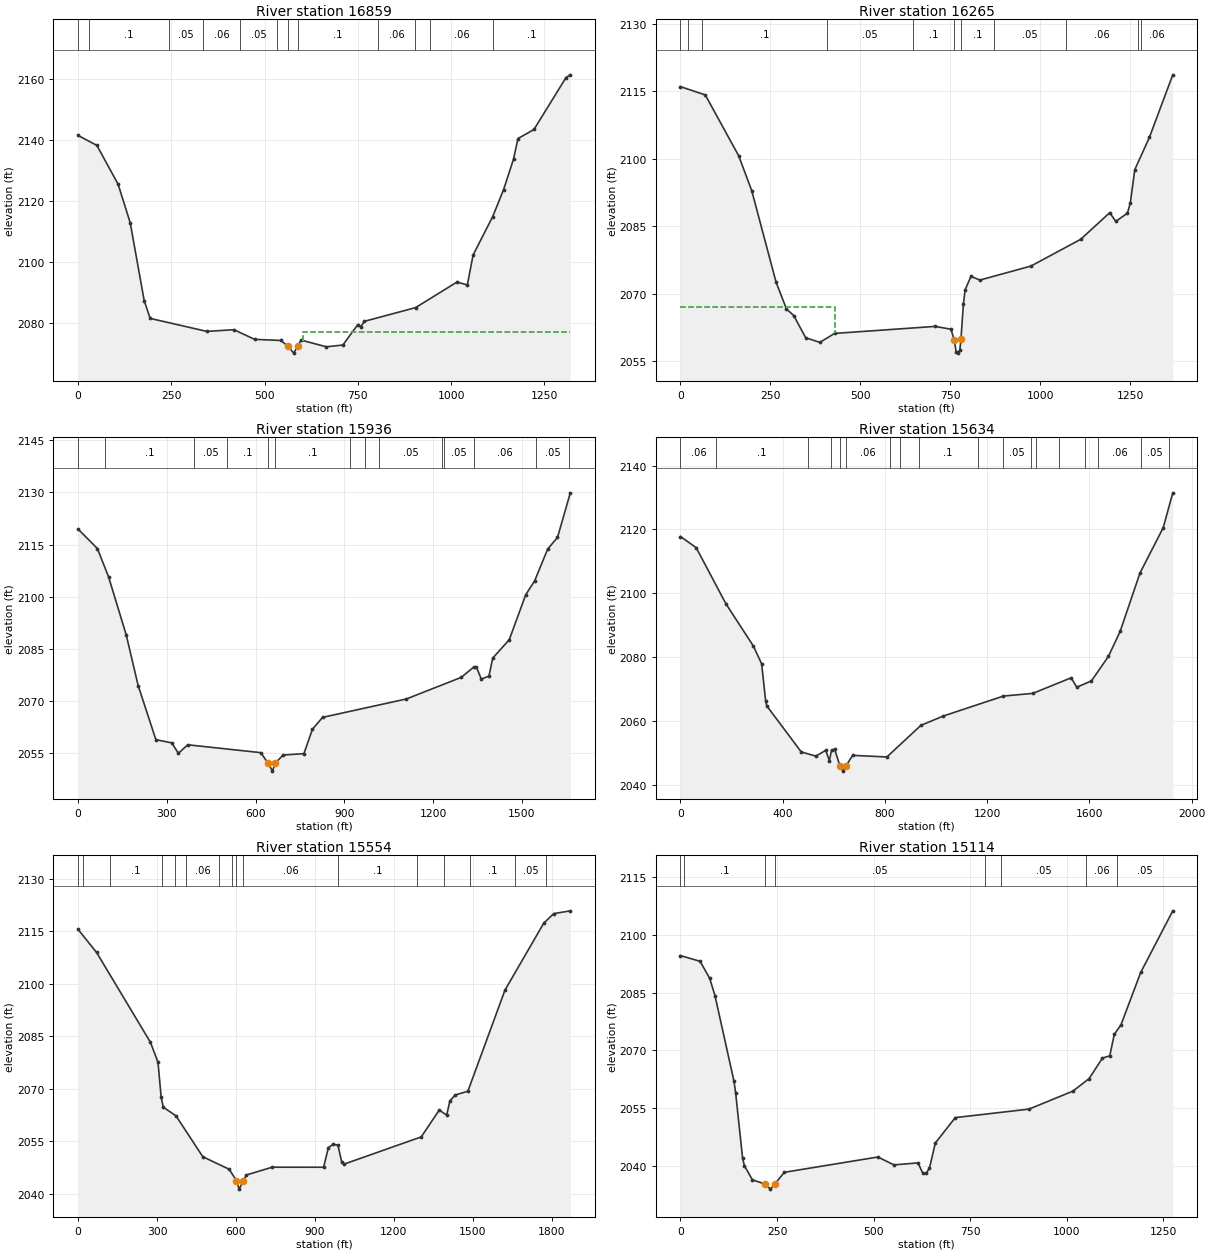
Type RM Length L Ch R = 1 ,16859   ,603.8,594.2,578.9
XS GIS Cut Line= 4
2299678.88687933676467.1036432892299750.21607765676625.973221375
2299724.27818735677214.4391075522300243.03599335677415.457757376
#Sta/Elev= 30
       0 2141.65    50.5 2138.39   107.5 2125.62   139.9 2112.99   177.4 2087.42
   193.4 2081.64   345.5 2077.37   417.6 2077.94   473.6 2074.76   543.5 2074.41
  563.492072.438     578 2070.25  588.792072.466   597.8 2074.53   665.8 2072.32
   709.9 2072.91   749.9 2079.63   757.9 2078.91   767.4 2080.68   904.6 2085.17
  1015.7 2093.56  1043.5 2092.62  1058.9 2102.43  1111.5 2115.05  1140.6 2123.86
  1167.2 2133.87  1179.2 2140.63  1222.1 2143.61  1307.9 2160.63  1319.5 2161.53
#Mann= 12 ,-1,0
       0     .05       0      30      .1       0  244.15     .05       0
  334.15     .06       0  434.15     .05       0  534.15      .1       0
  563.49    .045       0  588.79      .1       0  803.18     .06       0
  903.18     .05       0  943.18     .06       0 1113.18      .1       0
#XS Ineff= 2 , 0
                          604.04         2077.32
Permanent Ineff=
       F       F
Bank Sta=563.49,588.79
XS Rating Curve= 0 ,0
Exp/Cntr(USF)=0,0
Exp/Cntr=0.3,0.1

Type RM Length L Ch R = 1 ,16265   ,324.7,328.3,334
XS GIS Cut Line= 4
2299057.99418277676868.7001944912299094.91965159677183.377238615
2299480.07613994677459.566866577 2300048.1517462677359.227795095
#Sta/Elev= 30
       0 2116.01    68.9 2114.17   161.6 2100.65   197.8 2092.92   265.5 2072.55
   294.4 2066.58   314.6 2065.12   347.9 2060.17   387.3 2059.15     428 2061.14
   707.2  2062.7   751.5 2062.08  760.082059.774   766.2 2056.95   771.2 2056.76
   776.1 2057.46  779.27 2059.93     786 2067.67   790.9 2070.86   807.1 2073.84
   831.5    2073   973.7 2076.12  1111.8 2082.06  1192.5 2087.99  1209.3 2086.05
  1241.8 2087.88  1249.9 2090.22  1262.1 2097.55  1302.7 2104.72  1367.7 2118.64
#Mann= 11 ,-1,0
       0      .1       0      20     .05       0      60      .1       0
  406.84     .05       0  646.84      .1       0  760.08    .045       0
  779.27      .1       0  870.78     .05       0 1070.78     .06       0
 1270.78     .05       0 1280.78     .06       0
#XS Ineff= 2 , 0
          429.46 2067.04
Permanent Ineff=
       F       F
Bank Sta=760.08,779.27
XS Rating Curve= 0 ,0
Exp/Cntr(USF)=0,0
Exp/Cntr=0.3,0.1

Type RM Length L Ch R = 1 ,15936   ,310.3,302.3,299.2
XS GIS Cut Line= 4
2298801.58484882677104.034624926 2299003.3239956677255.338985008
2299244.69047478677734.469458602 2300060.6532738677417.450799382
#Sta/Elev= 30
       0 2119.45    65.5 2113.86   103.2 2105.71   162.7  2089.1   203.2 2074.49
   263.1 2058.95   316.9 2058.01   339.3 2055.02   370.7 2057.47   617.5 2055.21
  642.882052.142   657.3  2049.9  666.452052.187   693.2 2054.52   763.5 2054.93
   792.2  2061.9   826.4 2065.34    1110 2070.64  1294.5 2076.81  1337.4 2079.77
    1346 2079.91  1363.1 2076.35  1388.9 2077.19  1401.8 2082.39  1457.6 2087.66
  1513.3 2100.59  1543.4 2104.56  1587.5 2113.72  1620.6 2117.03    1664 2129.86
#Mann= 14 ,-1,0
       0     .06       0      90      .1       0  392.17     .05       0
  502.17      .1       0  642.88    .045       0  666.45      .1       0
  918.67     .06       0  968.67      .1       0 1018.67     .05       0
 1228.67     .06       0 1238.67     .05       0 1338.67     .06       0
 1548.67     .05       0 1658.67      .1       0
Bank Sta=642.88,666.45
XS Rating Curve= 0 ,0
Exp/Cntr(USF)=0,0
Exp/Cntr=0.3,0.1

Type RM Length L Ch R = 1 ,15634   ,79.5,80.1,77.5
XS GIS Cut Line= 4
2298682.89631839677243.828823812 2298672.0888641677591.468603525
2299118.79697482 677885.071111782300064.44922533677443.766728207
#Sta/Elev= 30
       0 2117.78    61.4  2114.3   177.4 2096.75   285.5  2083.4   317.5 2077.89
   333.1  2066.3   337.5 2064.71   472.4 2050.27   529.8 2048.95   568.1 2050.77
   582.5 2047.55   591.3 2050.88   603.3 2051.03  624.272045.775   635.1 2044.25
   646.6 2045.79   673.4  2049.2   807.4 2048.68   940.5 2058.59  1027.8 2061.51
  1263.5 2067.78  1378.3 2068.62  1528.3  2073.5  1550.4 2070.55  1607.8 2072.54
    1674 2080.19    1720 2088.05  1797.6 2106.35  1888.5 2120.55  1925.9 2131.48
#Mann= 18 ,-1,0
       0     .06       0     140      .1       0  497.81     .07       0
  587.81     .06       0  624.27    .045       0   646.6     .06       0
  817.81      .1       0  857.81     .06       0  932.36      .1       0
 1162.36     .06       0 1262.36     .05       0 1372.36     .06       0
 1392.36     .05       0 1482.36     .06       0 1582.36     .07       0
 1632.36     .06       0 1802.36     .05       0 1912.36      .1       0
Bank Sta=624.27,646.6
XS Rating Curve= 0 ,0
Exp/Cntr(USF)=0,0
Exp/Cntr=0.3,0.1

Type RM Length L Ch R = 1 ,15554   ,439.8,439.8,438.3
XS GIS Cut Line= 4
 2298633.0174707677262.9753632052298675.26883522677676.593984241
2299097.78248036677950.1159755722300042.87879187677843.375686272
#Sta/Elev= 30
       0 2115.53    70.6 2108.91   274.9 2083.27   303.8 2077.53   315.8 2067.54
   323.9 2064.69   372.1 2062.23     474 2050.54   574.1 2046.96     602 2043.72
   612.2 2041.28     628 2043.67   639.6 2045.33   737.9 2047.55     933 2047.54
     951 2053.13   969.1 2054.09   987.2 2053.87    1002 2048.93  1010.1 2048.41
  1303.9 2056.21  1372.3 2063.89  1400.5 2062.43  1412.6 2066.47  1432.7 2068.18
    1481 2069.26  1621.9 2098.16  1769.3  2117.3  1807.1 2120.02  1870.2 2120.82
#Mann= 16 ,-1,0
       0      .1       0      20     .06       0     120      .1       0
     320     .06       0     370      .1       0     410     .06       0
  535.77     .07       0  585.77     .06       0     602    .045       0
     628     .06       0  989.09      .1       0 1289.09     .06       0
 1389.09     .07       0 1489.09      .1       0 1659.09     .05       0
 1779.09     .06       0
Bank Sta=602,628
XS Rating Curve= 0 ,0
Exp/Cntr(USF)=0,0
Exp/Cntr=0.3,0.1

Type RM Length L Ch R = 1 ,15114   ,578.9,580.4,581
XS GIS Cut Line= 3
2298465.00034866678080.0821611552299427.18943733678574.051758718
2299561.09537734678713.798270391
#Sta/Elev= 30
       0 2094.64    50.7 2093.16    75.5 2088.76    89.3 2084.25   138.5 2062.02
     143 2058.84   160.9 2041.95   165.4 2040.07   186.3 2036.35   219.4 2035.26
   232.9 2033.94  244.362035.264   268.9 2038.31   511.2 2042.29   552.8 2040.24
   615.2 2040.76   627.1 2038.18     636 2038.03   644.9 2039.38     660 2045.92
   711.8 2052.53   902.8 2054.74  1016.3 2059.41  1058.2 2062.65    1093 2068.01
  1111.9 2068.59  1123.5 2074.14  1141.1 2076.69    1192 2090.26  1275.1 2106.28
#Mann= 8 ,-1,0
       0     .05       0      10      .1       0   219.4    .045       0
  244.36     .05       0     790     .07       0     830     .05       0
    1050     .06       0 1131.58     .05       0
Bank Sta=219.4,244.36
XS Rating Curve= 0 ,0
Exp/Cntr(USF)=0,0
Exp/Cntr=0.3,0.1

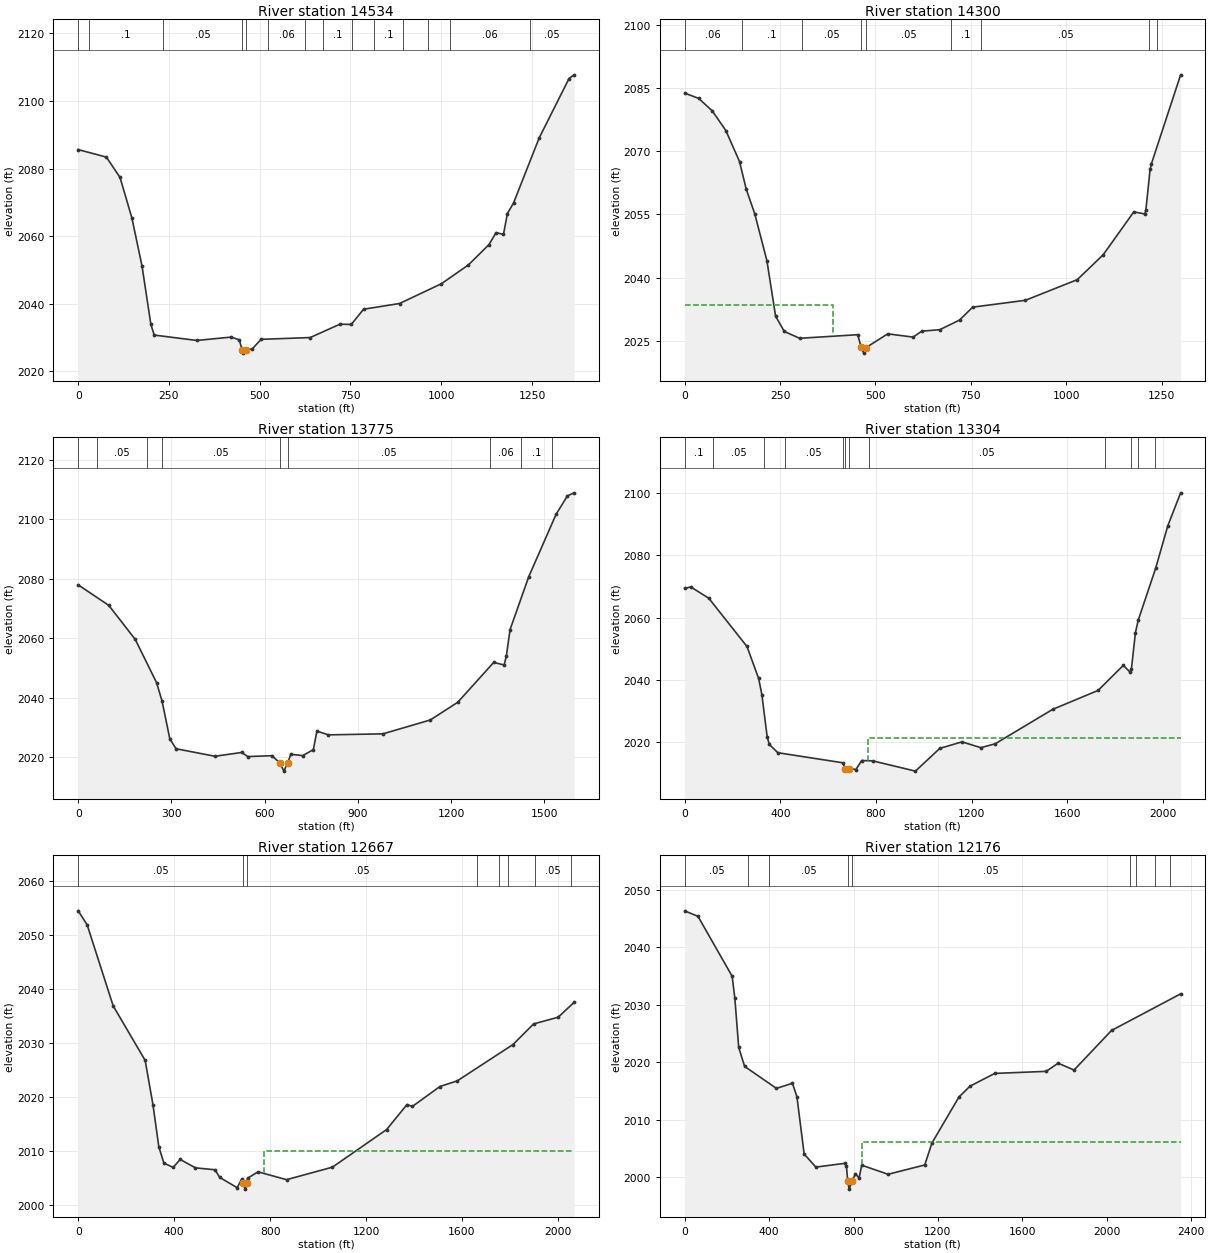
Type RM Length L Ch R = 1 ,14534   ,233.6,233.5,231.9
XS GIS Cut Line= 3
2298164.70338642678262.2209009832298269.20015297678437.569005399
2299118.44763803679230.790192778
#Sta/Elev= 30
       0  2085.6    77.6 2083.38   115.2 2077.36   147.7 2065.44   175.7 2051.21
   200.2 2033.86   209.4 2030.73   326.6 2029.14   421.7 2030.14   443.7 2029.31
  451.372026.443     455 2025.39   463.5 2026.44     479  2026.6   503.8 2029.47
     639    2030     721 2033.95   752.2 2033.88   786.1 2038.38   885.2 2040.07
  1000.5 2045.92  1074.8 2051.48  1131.4 2057.48  1151.2 2061.04  1171.5 2060.51
  1182.3 2066.67  1199.3 2069.82    1270 2089.09  1352.1 2106.63  1366.2 2107.72
#Mann= 14 ,-1,0
       0     .06       0      30      .1       0  234.12     .05       0
  451.37    .045       0   463.5     .05       0  524.12     .06       0
  624.12     .05       0  674.12      .1       0  754.12     .06       0
  814.12      .1       0  894.12     .06       0  964.12     .05       0
 1024.12     .06       0 1244.12     .05       0
Bank Sta=451.37,463.5
XS Rating Curve= 0 ,0
Exp/Cntr(USF)=0,0
Exp/Cntr=0.3,0.1

Type RM Length L Ch R = 1 ,14300   ,516.4,525.2,526.6
XS GIS Cut Line= 3
2298016.77326188678392.2866488072298112.64764566678587.948656527
2298937.04212251679288.620176031
#Sta/Elev= 30
       0 2083.74    36.6 2082.48    72.3 2079.53   107.9 2074.86   143.7 2067.51
   161.4 2060.93   183.6 2055.13   215.5    2044   238.3 2030.84     261 2027.21
   301.3 2025.59   453.5 2026.44   462.5 2023.51   469.2 2022.07  475.572023.397
   532.2 2026.64   598.7 2025.87   621.4 2027.28   668.7 2027.63   720.7 2029.93
   754.8 2032.97     893  2034.6  1028.9 2039.49  1096.9  2045.4  1177.1 2055.57
    1206 2055.07  1208.8 2056.08  1219.9 2065.69    1223  2066.9  1299.8 2088.07
#Mann= 9 ,-1,0
       0     .06       0     150      .1       0  307.89     .05       0
   462.5    .045       0  475.57     .05       0  697.89      .1       0
  777.89     .05       0 1217.89     .08       0 1237.89      .1       0
#XS Ineff= 2 , 0
           387.6 2033.37
Permanent Ineff=
       F       F
Bank Sta=462.5,475.57
XS Rating Curve= 0 ,0
Exp/Cntr(USF)=0,0
Exp/Cntr=0.3,0.1

Type RM Length L Ch R = 1 ,13775   ,470.7,471,472.7
XS GIS Cut Line= 3
2297753.25773192678638.8228791932298217.39588947679247.330737191
2299045.78726092679308.933226653
#Sta/Elev= 30
       0 2077.93    98.5 2071.02   183.6 2059.57   252.1 2045.06   269.6 2038.94
   294.7  2026.2   314.8 2022.81   440.1 2020.28   525.9 2021.56     546 2020.17
   623.1 2020.47   648.8 2018.08     662 2015.28  674.192018.049   684.2 2020.95
   722.4  2020.5   756.7 2022.51   768.1 2028.74   805.3 2027.48   980.7 2027.82
  1133.1 2032.49  1221.3 2038.43  1337.1 2051.84  1370.7 2050.99  1377.8 2054.01
  1389.8  2062.9    1450 2080.71  1537.6 2101.61  1574.3 2107.87    1596 2108.89
#Mann= 9 ,-1,0
       0      .1       0      60     .05       0     220      .1       0
     270     .05       0   648.8    .045       0  674.19     .05       0
 1325.31     .06       0 1425.31      .1       0 1525.31     .05       0
Bank Sta=648.8,674.19
XS Rating Curve= 0 ,0
Exp/Cntr(USF)=0,0
Exp/Cntr=0.3,0.1

Type RM Length L Ch R = 1 ,13304   ,636,637.6,624.5
XS GIS Cut Line= 3
2297506.85190434678850.4844924722297930.86025518679730.716677561
2298971.57807586679383.810737337
#Sta/Elev= 30
       0 2069.37    25.2 2069.87   100.7 2066.25   260.5 2050.77   309.3 2040.52
   322.7 2035.38   344.9  2021.9   353.6 2019.41   389.6 2016.72   660.1 2013.51
   672.42011.631  688.182011.655   716.2 2011.34   740.1 2014.21   786.5 2014.11
   964.9 2010.82    1067 2018.11  1159.5  2020.2  1238.6 2018.34  1298.7 2019.59
    1539 2030.62  1728.7 2036.68  1834.3 2044.72  1863.9 2042.46  1868.1 2043.45
  1884.9 2055.14  1896.3  2059.1  1969.3 2075.77  2020.2 2089.41    2074 2100.02
#Mann= 12 ,-1,0
       0      .1       0     120     .05       0     330      .1       0
     420     .05       0     660      .1       0   672.4    .045       0
  688.18      .1       0     770     .05       0 1757.03     .07       0
 1867.03     .05       0 1897.03     .06       0 1967.03      .1       0
#XS Ineff= 2 , 0
                          766.89         2021.57
Permanent Ineff=
       F       F
Bank Sta=672.4,688.18
XS Rating Curve= 0 ,0
Exp/Cntr(USF)=0,0
Exp/Cntr=0.3,0.1

Type RM Length L Ch R = 1 ,12667   ,490,491.1,479.1
XS GIS Cut Line= 4
2297166.58763715679440.6455160222297334.60475919679737.146319632
2297963.57081574680167.0724848682298683.68341562679524.654077045
#Sta/Elev= 30
       0 2054.54    37.4 2051.93   145.7 2036.93   279.1 2026.82   311.5 2018.64
   336.2 2010.78   357.2 2007.78     396 2006.99   425.1 2008.47   488.7  2006.9
   570.4 2006.55   589.8 2005.14   662.5 2003.23   681.1 2004.75  687.482004.062
   696.4 2002.96   701.7 2004.05   706.1 2004.97   749.7 2006.17   868.6 2004.71
  1059.8 2007.03  1285.8    2014  1370.7 2018.63  1393.4 2018.29  1508.1 2021.98
  1580.5 2023.03  1812.7 2029.76  1898.6 2033.58  2000.8 2034.82  2067.7 2037.58
#Mann= 8 ,-1,0
       0     .05       0  687.48    .045       0   701.7     .05       0
 1662.66     .06       0 1752.66     .05       0 1792.66     .06       0
 1902.66     .05       0 2052.66     .07       0
#XS Ineff= 2 , 0
                          775.19         2010.11
Permanent Ineff=
       F       F
Bank Sta=687.48,701.7
XS Rating Curve= 0 ,0
Exp/Cntr(USF)=0,0
Exp/Cntr=0.3,0.1

Type RM Length L Ch R = 1 ,12176   ,580.5,589.6,586.1
XS GIS Cut Line= 3
 2296721.0663702679939.4579556382298004.17359783680413.117989406
 2298609.0352372679639.250891982
#Sta/Elev= 30
       0  2046.3      63 2045.34   224.9 2034.93   237.8 2031.07     256 2022.56
     284 2019.26   434.9 2015.44   510.7 2016.33     532 2013.96   566.1 2004.03
   621.6 2001.76     758 2002.41   766.5 2001.94  772.72 1999.27   779.3 1997.93
   793.1 1999.35   809.2 2000.61   826.2 1999.86     839 2002.09   963.7 2000.51
  1137.5 2002.13  1171.6 2005.94  1299.5 2013.94  1352.2 2015.83  1469.2 2018.04
  1712.9  2018.4  1769.5 2019.82  1844.9 2018.63  2022.6 2025.51  2349.9 2031.87
#Mann= 9 ,-1,0
       0     .05       0     300     .08       0     400     .05       0
  772.72    .045       0   793.1     .05       0 2107.74     .06       0
 2137.74     .05       0 2227.74     .06       0 2297.74     .05       0
#XS Ineff= 2 , 0
                          841.64         2006.18
Permanent Ineff=
       F       F
Bank Sta=772.72,793.1
XS Rating Curve= 0 ,0
Exp/Cntr(USF)=0,0
Exp/Cntr=0.3,0.1

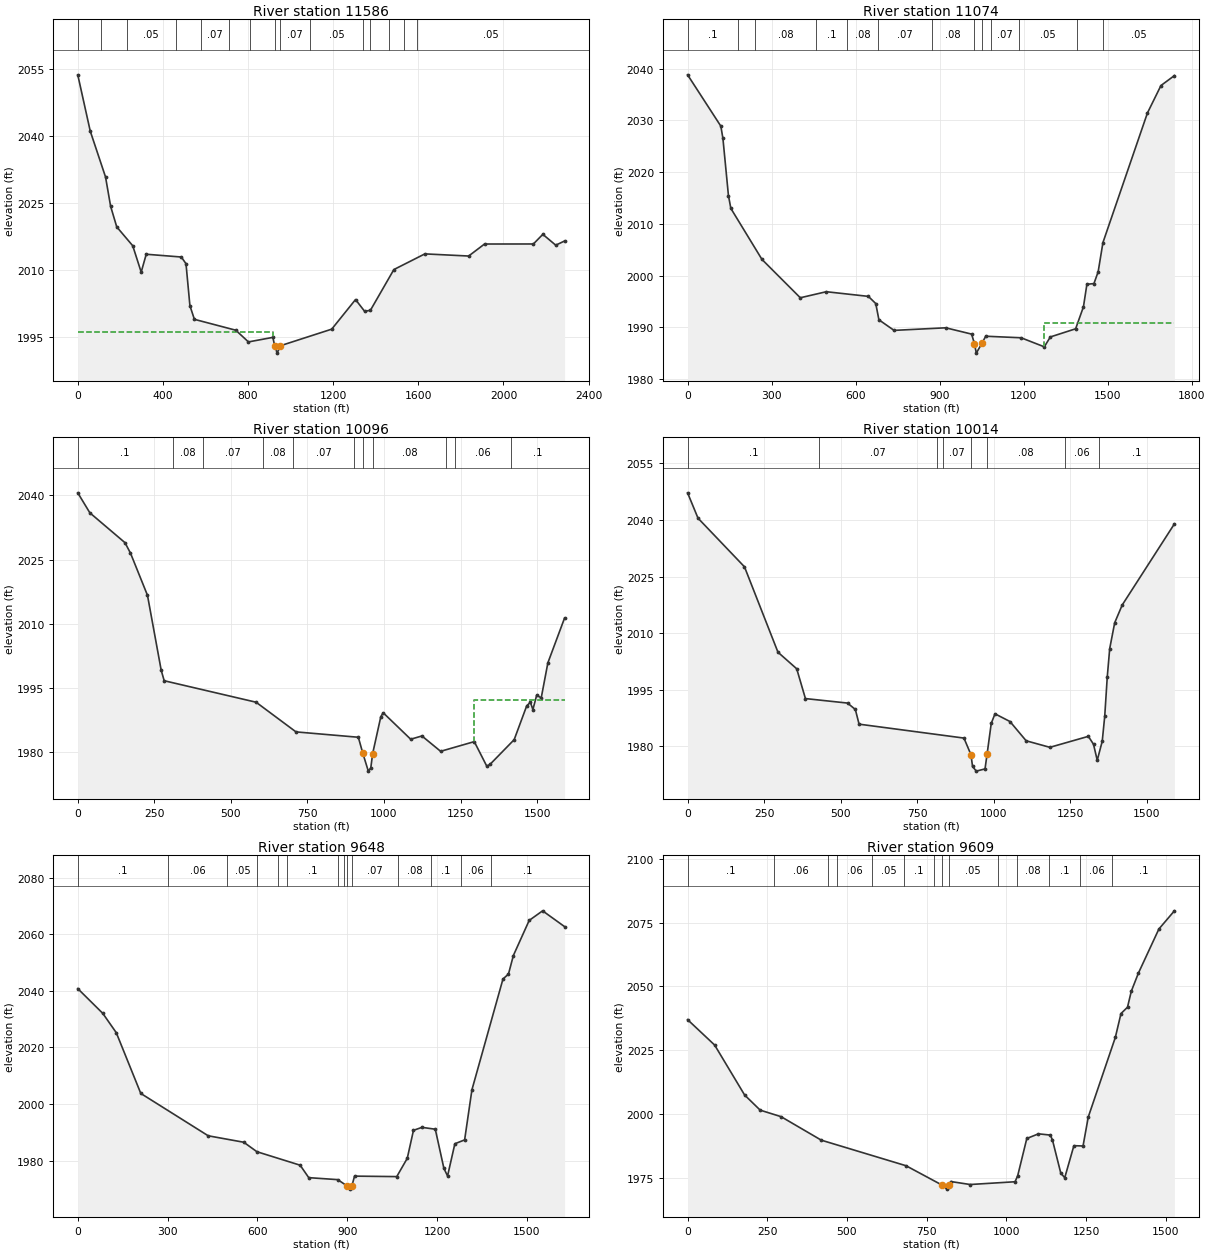
Type RM Length L Ch R = 1 ,11586   ,512.8,511.7,502.7
XS GIS Cut Line= 4
2296711.08417648680160.603629086 2297155.1298198680452.149025748
2297710.17932416680895.7471724832298338.06644723680059.925133994
#Sta/Elev= 30
       0 2053.75    58.7 2041.14   130.5 2030.87   154.4  2024.3   183.1 2019.69
   258.3 2015.46     298 2009.55   321.7 2013.56   486.5 2012.94   508.5 2011.44
   526.9 2002.04   547.9 1998.98   742.5 1996.54   801.9 1993.92   916.6 1994.94
  925.151993.049   936.8 1991.41  951.881993.064  1193.1 1996.78    1305 2003.41
  1347.8 2000.77    1375 2001.01  1485.1 2010.13  1630.7 2013.64  1836.4 2013.16
    1911 2015.85  2140.5 2015.86  2184.9 2018.02  2245.5 2015.59  2287.1 2016.53
#Mann= 15 ,-1,0
       0      .1       0     110     .06       0     230     .05       0
     460      .1       0   581.2     .07       0   711.2     .05       0
   811.2     .07       0  925.15    .045       0  951.88     .07       0
  1091.2     .05       0 1341.74     .06       0 1371.74     .05       0
 1461.74     .07       0 1531.74     .06       0 1591.74     .05       0
#XS Ineff= 2 , 0
          916.86 1996.24
Permanent Ineff=
       F       F
Bank Sta=925.15,951.88
XS Rating Curve= 0 ,0
Exp/Cntr(USF)=0,0
Exp/Cntr=0.3,0.1

Type RM Length L Ch R = 1 ,11074   ,948.8,978.8,992.8
XS GIS Cut Line= 4
2296626.61286678680408.7183689422296916.56435199681027.322106757
2297583.05269505681238.5136991532297798.83620637681521.801658249
#Sta/Elev= 30
       0 2038.83   118.8  2028.9   126.2 2026.53   145.9 2015.48   154.5 2012.99
   265.6 2003.12   402.5  1995.7   495.3 1996.87   645.5 1995.97     672 1994.58
   683.2 1991.44   737.3 1989.39   921.9 1989.89  1014.3 1988.67  1024.31986.832
    1031 1984.99  1050.8 1986.86  1064.6 1988.26    1191 1987.96  1273.8 1986.21
  1295.4 1988.12  1385.7  1989.7  1413.6 1993.95  1425.9  1998.3  1451.1 1998.45
  1466.1 2000.72  1483.2 2006.38  1642.1 2031.45  1690.4 2036.76  1738.4 2038.68
#Mann= 13 ,-1,0
       0      .1       0     180     .07       0     240     .08       0
     460      .1       0     570     .08       0     680     .07       0
  873.19     .08       0  1024.3    .045       0  1050.8     .08       0
 1083.19     .07       0 1183.19     .05       0 1392.33     .07       0
 1482.33     .05       0
#XS Ineff= 2 , 0
                         1272.69         1990.91
Permanent Ineff=
       F       F
Bank Sta=1024.3,1050.8
XS Rating Curve= 0 ,0
Exp/Cntr(USF)=0,0
Exp/Cntr=0.3,0.1

Type RM Length L Ch R = 1 ,10096   ,83.1,81.3,81.4
XS GIS Cut Line= 3
2296560.81873447680425.8971587892296649.76897556680870.648364205
2296436.71850615681986.873225947
#Sta/Elev= 30
       0 2040.55    39.6 2035.88   154.3 2028.92   172.2 2026.49   227.7 2016.65
   272.6 1999.14   282.3 1996.73   582.4 1991.72   712.7  1984.8   916.3 1983.55
  931.211979.763   948.9 1975.65     957  1976.4   963.1 1979.75   989.6  1988.3
   997.4 1989.27  1087.3 1983.09    1124 1983.85  1185.1 1980.27    1295 1982.53
  1335.7 1976.82  1346.2 1977.21  1425.3 1982.99  1466.3 1990.89  1478.3  1991.7
  1486.4    1990  1498.6 1993.32  1513.7 1992.76  1535.3  2000.9  1589.9 2011.36
#Mann= 11 ,-1,0
       0      .1       0     310     .08       0     410     .07       0
  603.56     .08       0  703.56     .07       0  903.56     .08       0
  931.21    .045       0   963.1     .08       0 1203.56      .1       0
 1233.56     .06       0 1413.56      .1       0
#XS Ineff= 2 , 0
                         1295.24         1992.17
Permanent Ineff=
       F       F
Bank Sta=931.21,963.1
XS Rating Curve= 0 ,0
Exp/Cntr(USF)=0,0
Exp/Cntr=0.3,0.1

Type RM Length L Ch R = 1 ,10014   ,340.7,366.6,372
XS GIS Cut Line= 3
2296483.02845419680399.7413342982296571.97869527680844.492539714
2296358.92822587681960.717401456
#Sta/Elev= 30
       0 2047.21    34.1 2040.49   185.8  2027.6   295.2 2004.96   356.4 2000.57
   384.9 1992.67   522.4 1991.48   547.9 1989.78   560.1 1985.89   902.6  1982.2
  925.421977.812   930.7 1974.67   942.9 1973.44   971.4 1974.03   978.1 1977.92
   991.8 1986.12    1004 1988.63  1052.9 1986.59  1105.8 1981.48  1183.2 1979.75
  1308.9 1982.66  1325.7 1980.56  1337.9 1976.31  1354.2 1981.36  1362.4 1988.03
  1370.6 1998.38  1378.6 2005.92  1394.9 2012.77  1419.4 2017.47  1589.9 2038.98
#Mann= 8 ,-1,0
       0      .1       0     430     .07       0  813.56     .05       0
  833.56     .07       0  925.42    .045       0   978.1     .08       0
 1233.56     .06       0 1343.56      .1       0
Bank Sta=925.42,978.1
XS Rating Curve= 0 ,0
Exp/Cntr(USF)=0,0
Exp/Cntr=0.3,0.1

Type RM Length L Ch R = 1 ,9648    ,38.6,38.3,37.6
XS GIS Cut Line= 4
2296451.07548014680431.4499116622296281.97017971681203.160608057
2295973.11813796681236.8810102262295876.16550938681753.373259101
#Sta/Elev= 30
       0 2040.79    83.7 2032.04   128.7 2025.22   210.6 2003.78   435.8 1988.83
   554.6 1986.55   598.4 1983.21   742.8 1978.45   771.6 1974.05   868.3 1973.35
   898.2 1971.24   908.5    1970   915.91971.233   924.6 1974.59  1065.6 1974.42
  1100.7 1980.88  1121.4 1990.75  1149.7 1991.81  1194.3 1991.15  1223.1 1977.31
  1235.3 1974.65  1259.7 1986.02  1292.3 1987.38  1316.7 2005.07  1420.4 2044.18
  1438.8 2045.93  1455.1 2052.47    1508 2064.87  1552.8 2068.25  1626.2 2062.67
#Mann= 14 ,-1,0
       0      .1       0     300     .06       0     500     .05       0
     600     .06       0     670     .05       0     700      .1       0
  870.02     .05       0  890.02     .07       0   898.2    .045       0
   915.9     .07       0 1070.02     .08       0 1180.71      .1       0
 1280.71     .06       0 1380.71      .1       0
Bank Sta=898.2,915.9
XS Rating Curve= 0 ,0
Exp/Cntr(USF)=0,0
Exp/Cntr=0.3,0.1

Type RM Length L Ch R = 1 ,9609    ,334.5,341.4,343.4
XS GIS Cut Line= 4
2296396.30531008 680458.02584164 2296250.6755551681165.568969805
2295953.90246338681208.3485844972295841.85114726681700.682933312
#Sta/Elev= 30
       0 2036.95    84.9 2026.99   178.9 2007.42   227.8 2001.48   293.2 1998.93
   419.4 1989.72   685.2  1979.7   797.6 1972.16   813.8 1970.53  818.511972.152
   825.9  1973.5   886.3 1972.34  1027.2 1973.42  1035.4 1975.72  1064.1 1990.37
  1100.7  1992.2    1138 1991.71  1144.7 1989.73  1170.7  1976.8  1183.1    1975
  1211.8 1987.55  1240.5 1987.44  1256.9 1998.79  1341.8 2029.98  1359.5 2039.32
    1380 2041.83  1391.9 2048.08    1414 2055.13  1478.4 2072.46  1527.1 2079.59
#Mann= 14 ,-1,0
       0      .1       0     270     .06       0     440     .05       0
     470     .06       0     580     .05       0     680      .1       0
  772.37     .05       0   797.6    .045       0  818.51     .05       0
  972.37     .07       0 1032.22     .08       0 1132.22      .1       0
 1232.22     .06       0 1332.22      .1       0
Bank Sta=797.6,818.51
XS Rating Curve= 0 ,0
Exp/Cntr(USF)=0,0
Exp/Cntr=0.3,0.1

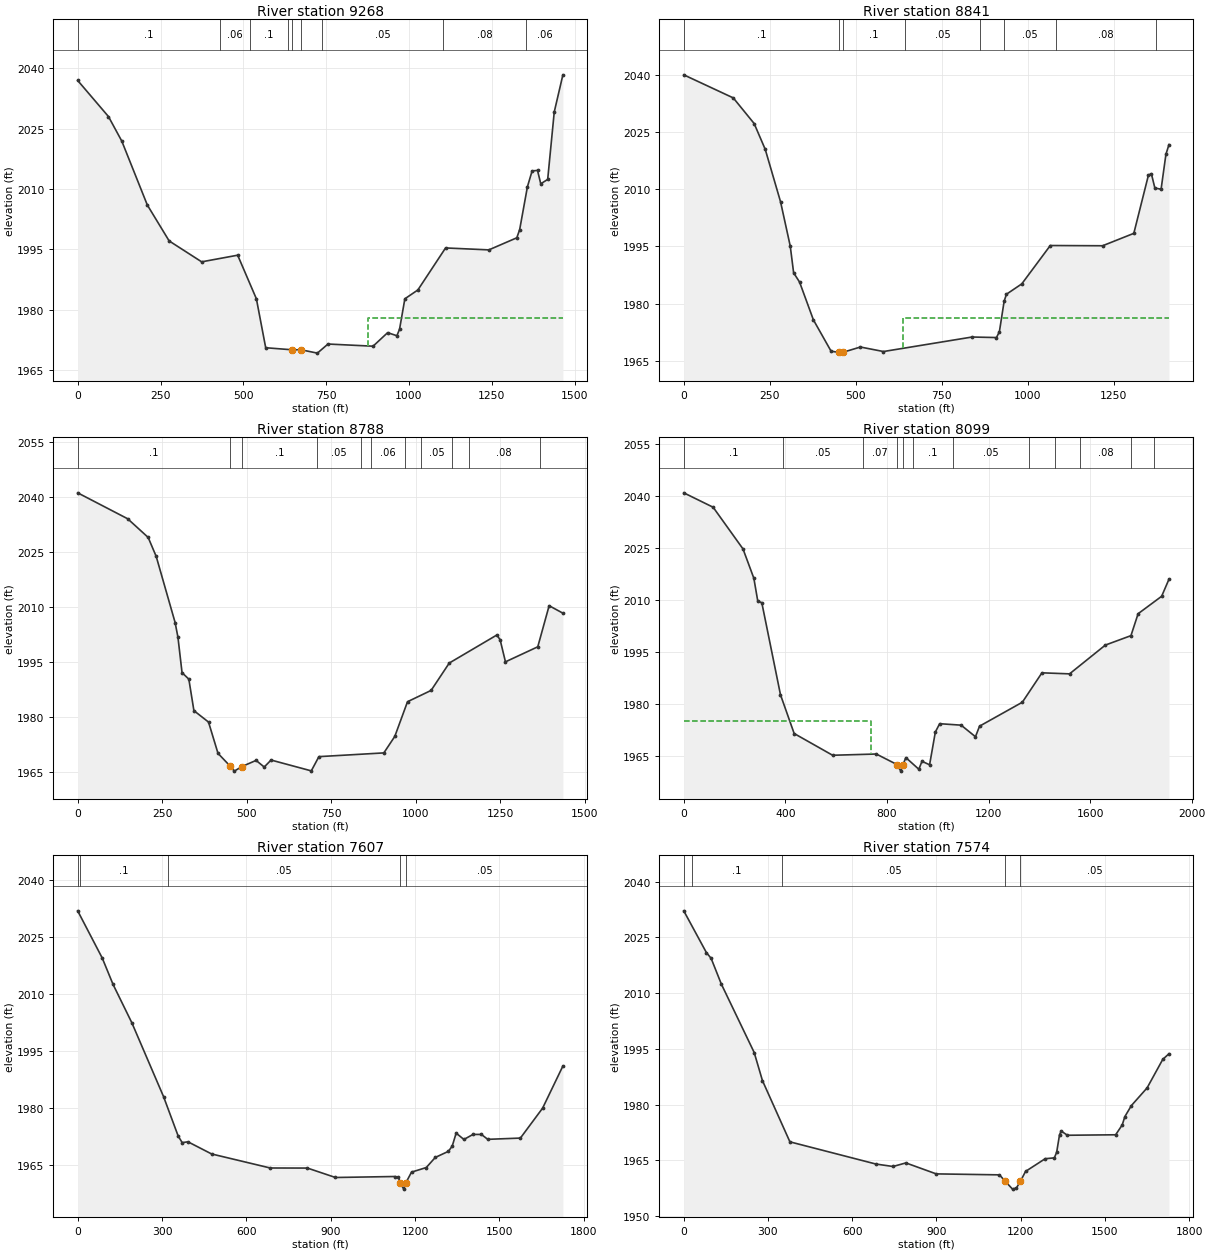
Type RM Length L Ch R = 1 ,9268    ,418,427.2,401.4
XS GIS Cut Line= 4
2296338.69936703680441.9423668862296091.74900416680940.020333619
2295654.66329712 680939.32765677  2295351.351691681300.312193339
#Sta/Elev= 30
       0 2036.93    92.9 2027.97   133.1 2021.88   210.2    2006   276.1 1997.08
   374.2 1991.89   482.9 1993.54   539.4 1982.71   567.5 1970.56  647.241970.046
   674.2 1970.05   723.5 1969.22   755.5 1971.48   891.5 1970.94   935.5  1974.3
   963.5 1973.54   971.5 1975.16   987.5 1982.71  1026.8 1984.91  1110.4 1995.34
    1241 1994.86  1325.4 1997.86    1334 1999.88  1357.5 2010.56  1371.6 2014.47
  1387.9 2014.59  1397.7 2011.27  1418.6 2012.36  1438.4 2029.11  1464.5 2038.33
#Mann= 9 ,-1,0
       0      .1       0     430     .06       0     520      .1       0
  635.94     .07       0  647.24    .045       0   674.2     .07       0
  735.94     .05       0 1103.02     .08       0 1353.02     .06       0
#XS Ineff= 2 , 0
                           875.3         1977.98
Permanent Ineff=
       F       F
Bank Sta=647.24,674.2
XS Rating Curve= 0 ,0
Exp/Cntr(USF)=0,0
Exp/Cntr=0.3,0.1

Type RM Length L Ch R = 1 ,8841    ,69.5,52.8,50.6
XS GIS Cut Line= 4
2296282.85777089680391.2552619592295966.46749173  680436.0647766
2295942.57541695680667.7346745342295303.12816018681240.543303662
#Sta/Elev= 30
       0 2039.95   144.1  2033.9   204.7 2027.19     237 2020.41   281.5 2006.68
   309.7 1995.07   319.5 1988.08   336.8 1985.65     377 1975.75   428.4 1967.55
  450.971967.229   457.2 1967.04  461.841967.229   513.7 1968.64   580.7 1967.46
   838.4 1971.26   909.3 1971.12   917.8 1972.65   931.6 1980.62   938.3 1982.47
   982.9 1985.18  1065.8 1995.23    1218 1995.17  1308.7 1998.42  1351.2 2013.67
  1359.7 2014.06  1369.9 2010.29    1388 2009.98  1402.1 2019.15  1410.9 2021.67
#Mann= 8 ,-1,0
       0      .1       0  450.97    .045       0  461.84      .1       0
  642.45     .05       0  862.45     .06       0  932.45     .05       0
 1082.45     .08       0 1372.45     .06       0
#XS Ineff= 2 , 0
                           636.1         1976.18
Permanent Ineff=
       F       F
Bank Sta=450.97,461.84
XS Rating Curve= 0 ,0
Exp/Cntr(USF)=0,0
Exp/Cntr=0.3,0.1

Type RM Length L Ch R = 1 ,8788    ,664.9,688.9,694.6
XS GIS Cut Line= 4
2296275.33084177680364.3102170062295933.17086339 680398.26933198
2295909.27878862680629.9392299132295269.83153184681202.747859042
#Sta/Elev= 30
       0 2041.24   147.9 2034.15   208.5 2029.05   232.3 2023.85   288.2 2005.79
   296.6 2001.76   308.7 1992.09   328.8 1990.32   343.8 1981.71     387 1978.59
   415.1 1970.03   451.3 1966.52   463.4 1965.18   485.9 1966.44   527.7 1968.11
   551.8  1966.3     572 1968.21     691 1965.25   713.5 1969.14   905.6 1970.16
     938 1974.67   975.6 1984.15  1045.4 1987.24  1099.1 1994.72  1239.8 2002.38
  1249.5 2001.09  1265.3 1995.05  1360.9 1999.16  1394.5 2010.39  1435.2 2008.35
#Mann= 11 ,-1,0
       0      .1       0   451.3    .045       0   485.9      .1       0
  706.74     .05       0  836.74      .1       0  866.74     .06       0
  966.74      .1       0 1016.74     .05       0 1106.74      .1       0
 1156.74     .08       0 1366.74      .1       0
Bank Sta=451.3,485.9
XS Rating Curve= 0 ,0
Exp/Cntr(USF)=0,0
Exp/Cntr=0.3,0.1

Type RM Length L Ch R = 1 ,8099    ,489.7,492,483.9
XS GIS Cut Line= 4
2296258.84619441680357.8573767322295897.31030961680176.384942639
2295348.53380574680349.8727672362295240.45926282 681273.91010917
#Sta/Elev= 30
       0 2040.87   115.7 2036.71   233.3 2024.67     276 2016.21   291.5 2009.59
   307.3 2009.16   380.9 1982.57   434.7 1971.39   586.1 1965.11   758.1 1965.47
   839.6 1962.43   854.6 1960.53  863.021962.404   874.6 1964.43   925.6 1961.07
     938 1963.37   967.9 1962.36   990.6 1971.82  1007.6 1974.22  1092.1  1973.8
  1148.5 1970.46  1164.6 1973.51  1333.1 1980.42  1410.3 1988.91    1519 1988.61
    1660 1996.92  1760.7 1999.64  1788.9 2005.97  1881.5    2011  1910.4 2015.93
#Mann= 12 ,-1,0
       0      .1       0     390     .05       0  704.52     .07       0
   839.6    .045       0  863.02     .07       0  904.52      .1       0
 1060.07     .05       0 1360.07     .06       0 1460.07     .05       0
 1560.07     .08       0 1760.07      .1       0 1850.07     .06       0
#XS Ineff= 2 , 0
          737.54 1974.98
Permanent Ineff=
       F       F
Bank Sta=839.6,863.02
XS Rating Curve= 0 ,0
Exp/Cntr(USF)=0,0
Exp/Cntr=0.3,0.1

Type RM Length L Ch R = 1 ,7607    ,34.4,33.3,41
XS GIS Cut Line= 4
2296130.39807338 679832.696797182295825.06905872680077.631061688
2295098.65442494  680126.28238822294578.58852085680438.321930655
#Sta/Elev= 30
       0 2031.78    87.3 2019.37   125.9 2012.41   192.6 2002.34   305.4 1982.91
   357.6 1972.51   371.8  1970.8   392.3 1971.01   476.5 1967.81     685 1964.12
   817.3  1964.1   917.1 1961.62    1127 1961.88  1140.7 1961.67 1148.111960.176
  1159.7 1958.56  1167.1 1960.18  1187.5 1963.03    1240 1964.24  1272.1  1966.9
  1318.7  1968.5  1332.3 1969.88  1346.3 1973.29  1373.9 1971.63  1406.2 1972.95
  1436.1 1972.95  1458.7 1971.66  1574.8 1971.99  1653.8 1979.86    1726 1990.95
#Mann= 5 ,-1,0
       0     .05       0      10      .1       0     320     .05       0
 1148.11    .045       0  1167.1     .05       0
Bank Sta=1148.11,1167.1
XS Rating Curve= 0 ,0
Exp/Cntr(USF)=0,0
Exp/Cntr=0.3,0.1

Type RM Length L Ch R = 1 ,7574    ,24.2,33.7,48.6
XS GIS Cut Line= 4
2296125.36517754679820.9533735392295826.74669067680055.821846355
 2295090.2662652680094.4073811752294565.16746526 680406.44692363
#Sta/Elev= 30
       0 2032.12    80.8 2020.87    97.4 2019.36   133.8 2012.43   250.9 1994.01
   280.2 1986.47   378.1 1969.98   684.3 1964.01   745.2 1963.35   791.2 1964.31
   899.2 1961.36  1124.5  1961.1 1145.651959.326    1171 1957.26    1185 1957.59
  1198.9 1959.34  1217.3 1962.02  1287.3 1965.44  1319.9 1965.67  1328.2 1967.17
  1338.5 1971.92  1344.8 1972.86  1366.4 1971.75  1538.3 1971.88  1561.7 1974.53
  1571.2 1976.78  1594.4 1979.74  1650.3 1984.49  1706.1 1992.16  1728.2 1993.68
#Mann= 5 ,-1,0
       0     .05       0      30      .1       0     350     .05       0
 1145.65    .045       0  1198.9     .05       0
Bank Sta=1145.65,1198.9
XS Rating Curve= 0 ,0
Exp/Cntr(USF)=0,0
Exp/Cntr=0.3,0.1