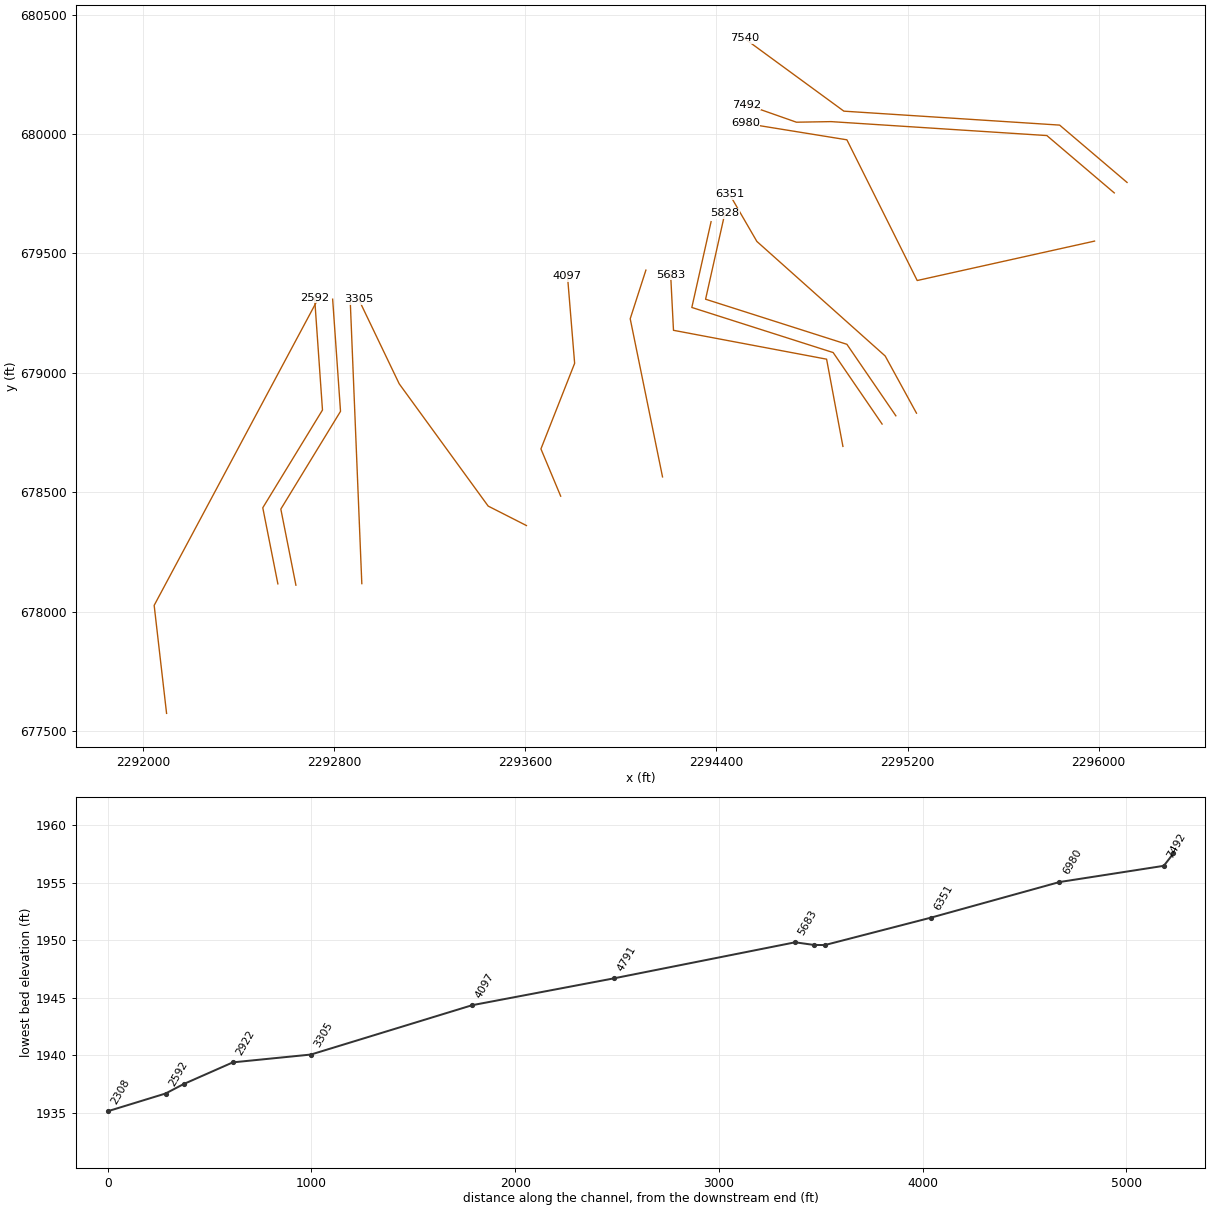
HEC-RAS study KINGSRN.prj: KINGSRN

--- KINGSRN.g01 (geometry) --- (continued)

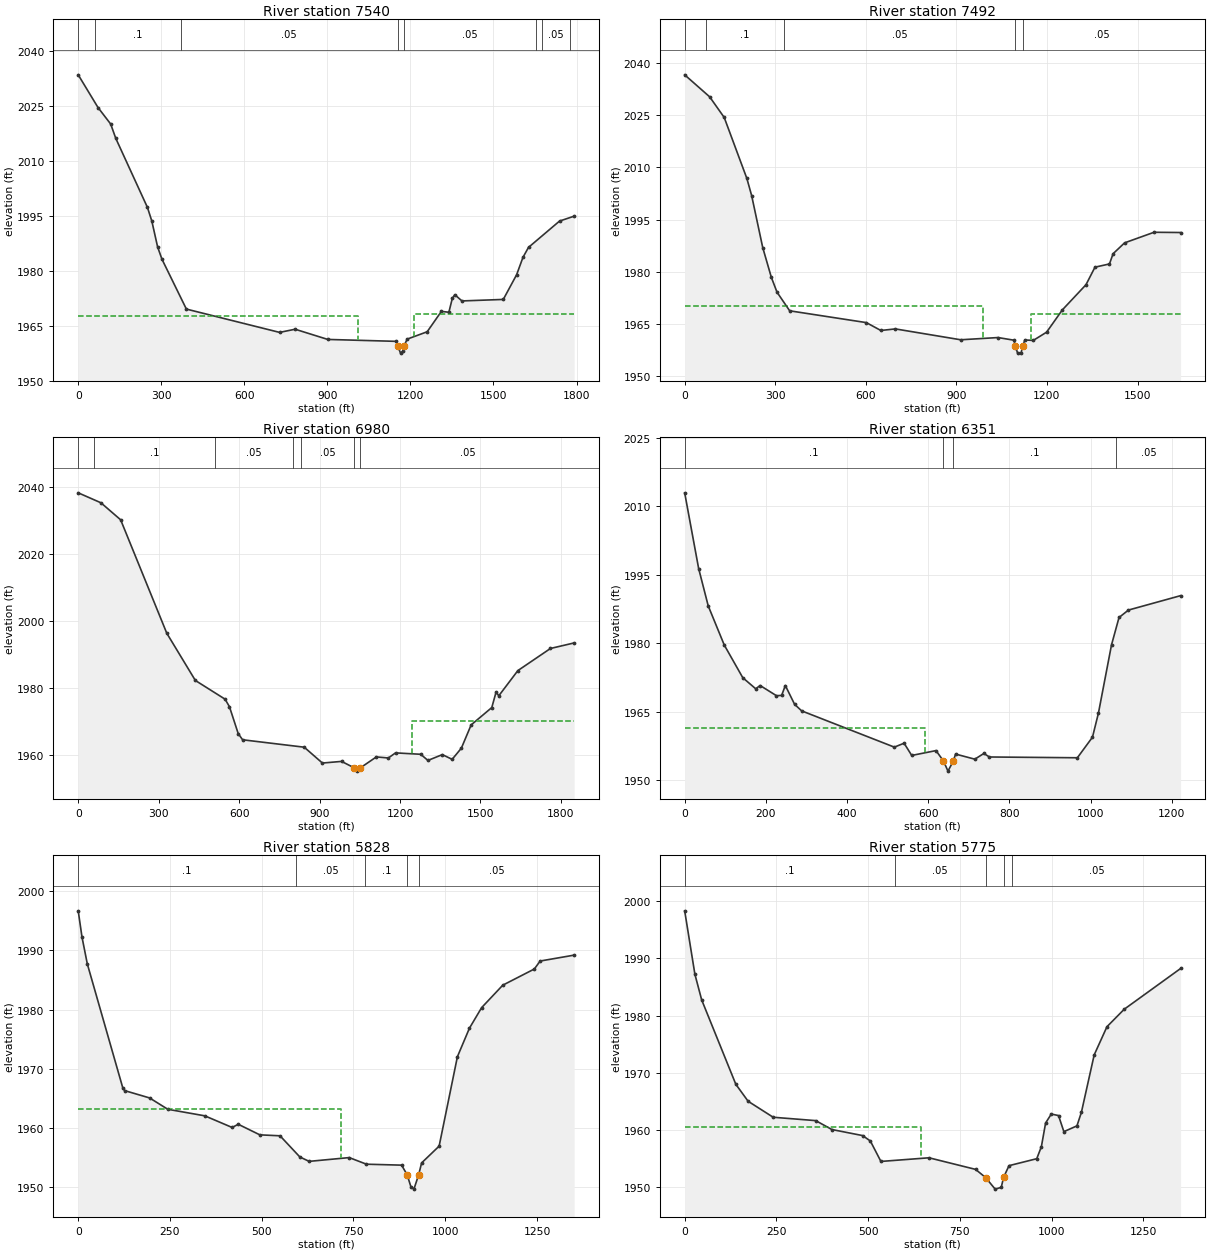
Type RM Length L Ch R = 1 ,7540    ,47.8,47.4,47.5
XS GIS Cut Line= 4
2296118.61051816679797.2657132022295836.53596114680037.191198476
2294933.57315508 680095.551451652294516.94579214680400.321662674
#Sta/Elev= 30
       0 2033.39    71.5 2024.48   117.2 2019.99   135.7 2016.08     250 1997.27
   265.8 1993.57   286.8  1986.5   302.5 1983.15   390.7 1969.56   727.4 1963.21
   783.5 1964.07   901.5 1961.29  1148.3 1960.77  1154.41959.464  1164.3 1957.56
  1172.1 1958.08  1176.3 1959.47  1188.4 1961.38  1260.5 1963.38  1311.8 1968.93
  1338.9  1968.7  1351.2 1972.45  1360.3 1973.48  1386.1 1971.78  1535.4 1972.19
  1583.6 1978.92  1606.5 1983.66  1626.5 1986.37  1738.6 1993.54  1791.4 1994.88
#Mann= 8 ,-1,0
       0     .05       0      60      .1       0     370     .05       0
  1154.4    .045       0  1176.3     .05       0 1655.16     .06       0
 1675.16     .05       0 1775.16     .06       0
#XS Ineff= 2 , 0
         1012.18 1967.72 1211.52         1968.09
Permanent Ineff=
       F       F
Bank Sta=1154.4,1176.3
XS Rating Curve= 0 ,0
Exp/Cntr(USF)=0,0
Exp/Cntr=0.3,0.1

Type RM Length L Ch R = 1 ,7492    ,510.3,512.1,478.8
XS GIS Cut Line= 5
2296065.11361941 679753.49552332 2295783.0390624679993.421008594
2294880.07625634680051.781261769 2294735.0049065680049.351852785
2294525.05138286680123.110460094
#Sta/Elev= 30
       0 2036.71    82.7 2030.37     131 2024.41     206 2006.83   221.8 2001.91
   258.5 1986.93     287 1978.35   305.8 1974.06   347.8 1968.68   601.7 1965.28
   649.8 1963.01   697.9 1963.46   914.3 1960.33  1037.9 1960.97  1090.7 1960.21
  1095.7 1958.54  1102.7 1956.48  1114.7 1956.63 1119.781958.557  1126.8 1960.27
  1154.8 1960.15  1198.9 1962.52    1251 1968.94  1329.4 1976.21  1359.1 1981.26
  1407.1 1982.19  1419.1 1985.14  1457.2 1988.27  1554.7 1991.32  1642.8 1991.25
#Mann= 5 ,-1,0
       0     .05       0      70      .1       0     330     .05       0
  1095.7    .045       0 1119.78     .05       0
#XS Ineff= 2 , 0
           988.7 1969.96 1148.17         1967.72
Permanent Ineff=
       F       F
Bank Sta=1095.7,1119.78
XS Rating Curve= 0 ,0
Exp/Cntr(USF)=0,0
Exp/Cntr=0.3,0.1

Type RM Length L Ch R = 1 ,6980    ,622,629.7,626.1
XS GIS Cut Line= 4
2295982.61671832679551.7563765442295240.40809242679386.810011878
2294946.16793006679975.6605880582294521.01731152680044.488498354
#Sta/Elev= 30
       0 2038.34    84.7 2035.36   158.2 2030.27   330.3 1996.32   436.8  1982.2
   547.7 1976.59   563.9 1974.35   596.7 1966.29     613 1964.45   842.8 1962.23
   910.5 1957.49   982.1 1957.98 1029.07 1956.06  1038.2 1955.07 1052.541956.074
  1111.7 1959.32  1156.5 1959.01  1183.3 1960.53  1277.2 1960.11    1304 1958.27
  1357.7 1960.01  1394.4  1958.6  1428.7 1961.94  1465.2  1968.9  1542.2 1974.09
  1558.4 1978.79  1568.1 1977.59  1639.4 1985.15    1761 1991.77  1849.3 1993.43
#Mann= 7 ,-1,0
       0     .05       0      60      .1       0     510     .05       0
  800.32      .1       0  830.32     .05       0 1029.07    .045       0
 1052.54     .05       0
#XS Ineff= 2 , 0
                         1244.74         1969.96
Permanent Ineff=
       F       F
Bank Sta=1029.07,1052.54
XS Rating Curve= 0 ,0
Exp/Cntr(USF)=0,0
Exp/Cntr=0.3,0.1

Type RM Length L Ch R = 1 ,6351    ,502.9,522.2,518.6
XS GIS Cut Line= 4
2295237.40931857678831.6970756992295106.42778547679070.962584563
2294569.48235421679550.3095314692294454.71746772 679748.36333353
#Sta/Elev= 30
       0 2012.99    34.4  1996.4      58  1988.2    97.5 1979.62   143.1 1972.46
     175 1970.03   185.8 1970.75     226 1968.52   238.8 1968.58   247.9 1970.75
   270.7 1966.63   288.1 1965.19   516.4 1957.24   540.4  1958.1   559.2 1955.42
     619 1956.48  637.261954.223   648.5 1951.98   661.9 1954.25   667.2 1955.72
   714.6  1954.6   736.9 1955.85   750.6 1955.08   967.2 1954.91  1004.4 1959.42
  1019.1 1964.71  1051.3 1979.66  1069.8 1985.66    1093 1987.29  1221.5 1990.45
#Mann= 4 ,-1,0
       0      .1       0  637.26    .045       0   661.9      .1       0
 1062.55     .05       0
#XS Ineff= 2 , 0
           590.7 1961.54
Permanent Ineff=
       F       F
Bank Sta=637.26,661.9
XS Rating Curve= 0 ,0
Exp/Cntr(USF)=0,0
Exp/Cntr=0.3,0.1

Type RM Length L Ch R = 1 ,5828    ,59.9,53.3,52.5
XS GIS Cut Line= 4
2295151.04763012678820.6843096832294946.23385312679119.850500806
2294354.80530605679308.5553290532294435.35004982679667.554758401
#Sta/Elev= 30
       0 1996.71    10.3 1992.27    24.8 1987.72   121.8 1966.66   126.6 1966.27
   194.5 1965.03   244.1 1963.11   344.9    1962   419.4 1960.03   436.1 1960.57
   494.9 1958.78   549.9 1958.62     604 1955.03   629.2 1954.29   738.4 1954.93
   785.4 1953.81   881.2 1953.65   896.31952.004   906.3 1950.03   914.7 1949.59
   927.3 1951.95   935.7 1954.03   983.4 1956.87  1033.2 1972.01    1066 1976.84
  1099.2 1980.32  1156.8 1984.12  1242.8 1986.86  1258.7 1988.21  1351.3 1989.21
#Mann= 5 ,-1,0
       0      .1       0  592.56     .05       0  782.56      .1       0
   896.3    .045       0   927.3     .05       0
#XS Ineff= 2 , 0
          714.73 1963.15
Permanent Ineff=
       F       F
Bank Sta=896.3,927.3
XS Rating Curve= 0 ,0
Exp/Cntr(USF)=0,0
Exp/Cntr=0.3,0.1

Type RM Length L Ch R = 1 ,5775    ,89,92.6,95.1
XS GIS Cut Line= 4
2295093.51567029678786.1651337842294888.70189329679085.331324907
2294297.27334622679274.0361531552294377.81808999679633.035582503
#Sta/Elev= 30
       0 1998.35    27.9 1987.22    46.3 1982.75   139.4 1967.96   172.9 1964.99
   241.2 1962.19   357.1  1961.6   401.1 1960.04   484.9 1958.98   505.9 1958.03
   534.7 1954.45   665.7 1955.09   792.6 1953.06   819.9 1951.63     846  1949.6
   862.6 1949.91  868.881951.652   883.7 1953.71   959.3 1954.93   971.9 1957.03
   983.4 1961.18   998.9 1962.75  1018.6 1962.49  1033.2 1959.67  1068.8 1960.68
  1080.9 1963.04  1115.8 1973.11  1150.6 1978.05  1197.6 1981.11  1351.3 1988.25
#Mann= 5 ,-1,0
       0      .1       0  572.56     .05       0   819.9    .045       0
  868.88      .1       0  892.56     .05       0
#XS Ineff= 2 , 0
          644.96 1960.45
Permanent Ineff=
       F       F
Bank Sta=819.9,868.88
XS Rating Curve= 0 ,0
Exp/Cntr(USF)=0,0
Exp/Cntr=0.3,0.1

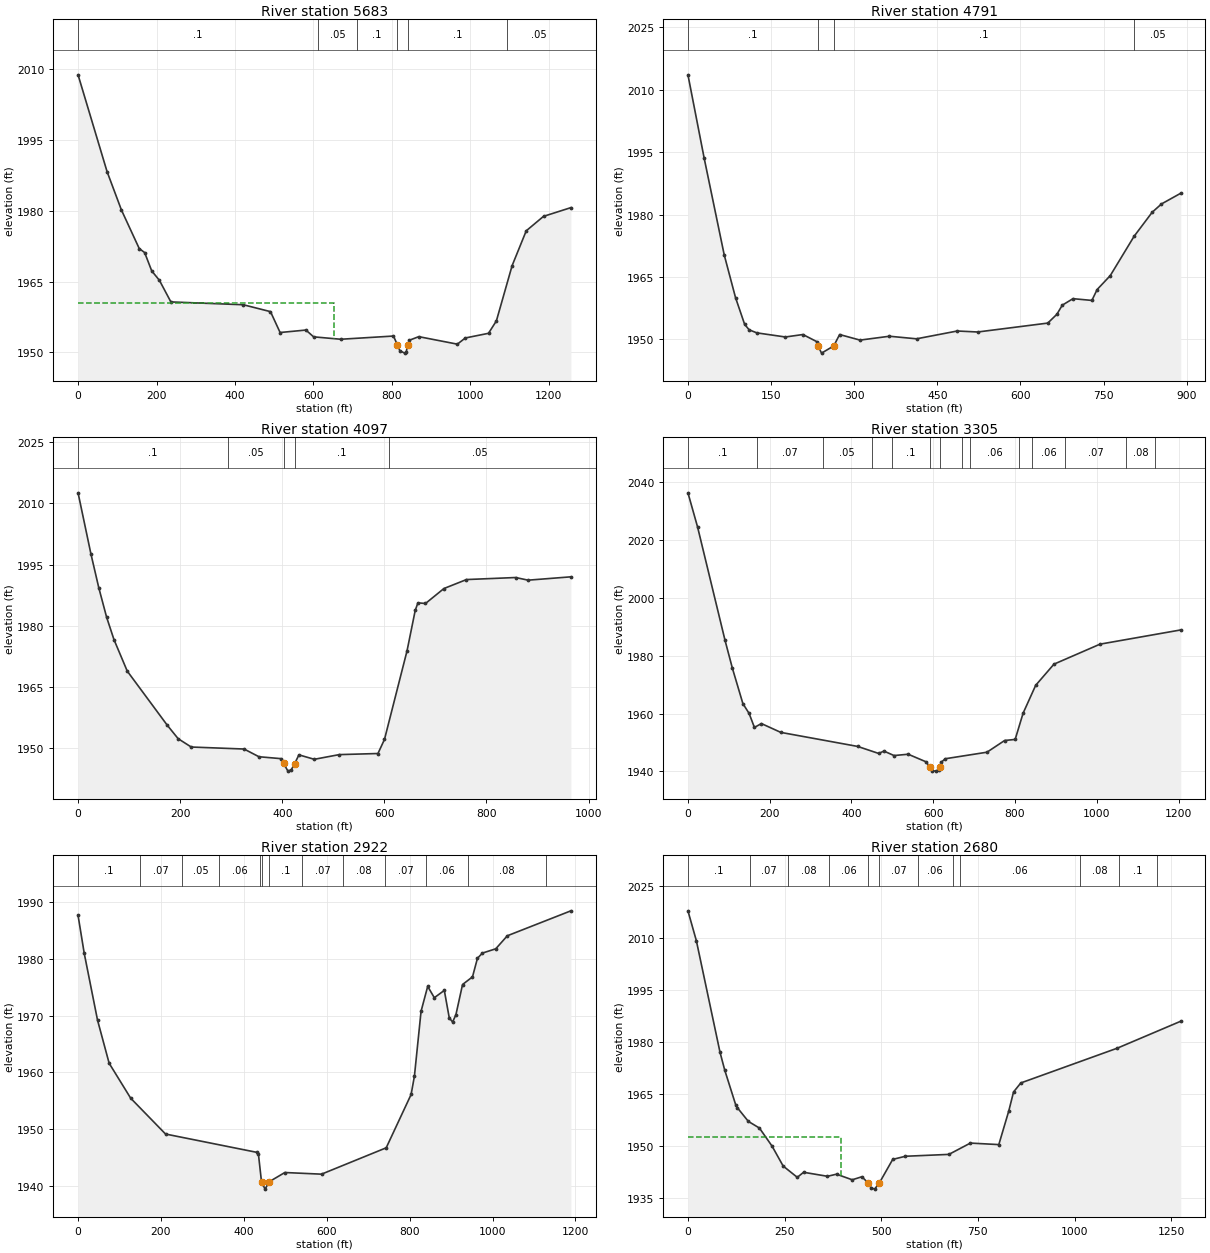
Type RM Length L Ch R = 1 ,5683    ,895.1,891.3,875.9
XS GIS Cut Line= 4
2294929.56009264678692.5837732282294861.27859642679057.627156837
2294220.48301656679178.4328809092294208.66506529679410.852589178
#Sta/Elev= 30
       0  2008.8    73.9  1988.3   110.5 1980.17     156 1971.98   169.7 1971.14
   187.8 1967.25   207.4 1965.25   236.6 1960.68   421.3 1960.08   490.5 1958.62
     515  1954.2   580.8 1954.72   600.4 1953.28   669.6 1952.77     804 1953.45
   813.7 1951.63   820.2 1950.35   832.5 1949.83   836.5 1950.05   840.11951.648
   844.8 1952.57   868.5 1953.32   966.8 1951.73   987.1 1953.04  1046.2 1954.03
  1066.3 1956.66  1106.4 1968.37  1142.4 1975.75  1186.4 1978.81  1256.2 1980.66
#Mann= 6 ,-1,0
       0      .1       0  611.37     .05       0  711.37      .1       0
   813.7    .045       0   840.1      .1       0 1093.46     .05       0
#XS Ineff= 2 , 0
          652.71 1960.45
Permanent Ineff=
       F       F
Bank Sta=813.7,840.1
XS Rating Curve= 0 ,0
Exp/Cntr(USF)=0,0
Exp/Cntr=0.3,0.1

Type RM Length L Ch R = 1 ,4791    ,687.9,694.4,683.4
XS GIS Cut Line= 3
2294174.63239173678564.985564134  2294039.382505679226.790835137
2294105.03778982679430.322218084
#Sta/Elev= 30
       0 2013.59    29.4 1993.48    65.5 1970.29    85.9 1960.02   102.3 1953.61
   110.4  1952.3   124.3 1951.56   175.8 1950.57   207.5 1951.16   232.8 1949.43
  234.96 1948.34   241.1 1946.69   263.11948.422   273.7 1951.16   310.5 1949.82
   363.6 1950.75   412.5 1950.13     486 1952.01   522.8 1951.77   649.3 1953.91
   665.7 1956.02   675.5 1958.22   694.8 1959.78   728.9 1959.36   738.4 1961.98
   762.1 1965.33   805.1 1974.78   837.7 1980.55   854.5 1982.55   889.3 1985.13
#Mann= 4 ,-1,0
       0      .1       0  234.96    .045       0   263.1      .1       0
  805.48     .05       0
Bank Sta=234.96,263.1
XS Rating Curve= 0 ,0
Exp/Cntr(USF)=0,0
Exp/Cntr=0.3,0.1

Type RM Length L Ch R = 1 ,4097    ,773.5,791.4,797.5
XS GIS Cut Line= 4
2293748.45956839678484.3048021172293665.78254306678682.081215654
2293806.81982157679040.3483254232293776.95255437679405.057656401
#Sta/Elev= 30
       0 2012.61    25.3 1997.57    40.6 1989.33    55.9 1982.12    70.3 1976.63
    96.3  1968.9   174.4 1955.67     196 1952.32   221.7 1950.27   325.2 1949.78
   354.3 1947.89   397.5 1947.42   402.5 1946.26   411.1 1944.36   417.5 1944.67
     424 1946.13   432.6 1948.35   462.7 1947.26   511.6 1948.41   587.4 1948.68
   600.2 1952.14   644.4 1973.88   660.4 1983.78   665.7 1985.63   680.5 1985.47
   716.6 1989.14   760.8 1991.34   857.1 1991.84   881.5 1991.19   965.3 1992.01
#Mann= 5 ,-1,0
       0      .1       0  294.36     .05       0   402.5    .045       0
     424      .1       0  609.39     .05       0
Bank Sta=402.5,424
XS Rating Curve= 0 ,0
Exp/Cntr(USF)=0,0
Exp/Cntr=0.3,0.1

Type RM Length L Ch R = 1 ,3305    ,387.5,383.3,376.5
XS GIS Cut Line= 4
 2293605.0983111678361.4010021192293444.94985092678442.817157783
  2293072.651063678954.5501184932292902.72185668679308.962569564
#Sta/Elev= 30
       0 2036.39    23.5  2024.6    90.8 1985.29   108.7  1975.7   134.4 1963.44
   149.6 1960.04   162.6 1955.19   179.7 1956.53   227.1 1953.48   415.1 1948.62
   466.5 1946.19   479.4 1947.01   504.1 1945.46   538.7 1945.92   582.1 1943.31
   591.4 1941.55   597.1 1940.23   605.7 1940.07   612.9 1940.48   615.41941.609
     620 1943.21   629.7 1944.36   731.5 1946.62   774.6 1950.67   800.4 1951.04
   819.8 1960.11   850.6 1969.77   895.3 1977.09  1007.9 1984.01  1205.5 1988.94
#Mann= 14 ,-1,0
       0      .1       0     170     .07       0  329.66     .05       0
  449.66     .07       0  499.66      .1       0   591.4    .045       0
   615.4      .1       0  669.66     .07       0  689.66     .06       0
  809.66      .1       0  842.49     .06       0  922.49     .07       0
 1072.49     .08       0 1142.49     .07       0
Bank Sta=591.4,615.4
XS Rating Curve= 0 ,0
Exp/Cntr(USF)=0,0
Exp/Cntr=0.3,0.1

Type RM Length L Ch R = 1 ,2922    ,249.3,241.9,233.3
XS GIS Cut Line= 2
2292916.18456462678118.2591294972292867.54390429679306.321690277
#Sta/Elev= 30
       0 1987.68    14.9 1980.99      47  1969.2      75  1961.6     127 1955.43
   211.1 1949.11   431.3 1945.88   435.3  1945.5  442.711940.612   451.3 1939.39
  461.441940.702   498.9 1942.32   587.4 1942.03   743.5 1946.68   803.6 1956.09
   811.6 1959.34   827.6 1970.77   843.6 1975.16   859.6 1973.16   883.7 1974.45
   895.7 1969.58   903.7 1968.88   911.7 1970.16   927.7 1975.49   951.7 1976.84
   963.7 1980.13   975.8 1981.04  1007.8 1981.79  1035.8 1984.09  1189.1 1988.49
#Mann= 13 ,-1,0
       0      .1       0     150     .07       0     250     .05       0
     340     .06       0     440      .1       0  442.71    .045       0
  461.44      .1       0     540     .07       0     640     .08       0
     740     .07       0     840     .06       0     940     .08       0
    1130     .07       0
Bank Sta=442.71,461.44
XS Rating Curve= 0 ,0
Exp/Cntr(USF)=0,0
Exp/Cntr=0.3,0.1

Type RM Length L Ch R = 1 ,2680    ,88.1,88.6,83
XS GIS Cut Line= 4
2292640.36808535678111.8198376042292577.22439569678430.283663706
2292827.05377651678839.3449575792292794.10924278679308.804563298
#Sta/Elev= 30
       0 2017.94    21.8 2009.29    82.9 1977.08    95.2 1971.88   123.7 1961.81
   127.8 1961.03   156.3 1957.07   184.9 1955.15   217.5 1949.94   246.3 1944.17
   282.8 1940.91   299.1 1942.37   360.9 1941.21   384.3 1941.82   424.9  1940.2
   449.9 1941.08  466.331939.253   473.4 1937.94   482.7  1937.5   494.8 1939.24
   529.6 1946.09   562.4    1947   674.9 1947.54   730.5 1950.81     804 1950.37
   829.9 1960.15   842.1 1965.58   860.9 1968.19  1110.6 1978.25  1274.6 1986.03
#Mann= 12 ,-1,0
       0      .1       0     160     .07       0     260     .08       0
  364.66     .06       0  466.33    .045       0   494.8     .07       0
  594.66     .06       0  684.66     .07       0  704.66     .06       0
 1013.98     .08       0 1113.98      .1       0 1213.98     .08       0
#XS Ineff= 2 , 0
           396.9 1952.58
Permanent Ineff=
       F       F
Bank Sta=466.33,494.8
XS Rating Curve= 0 ,0
Exp/Cntr(USF)=0,0
Exp/Cntr=0.3,0.1

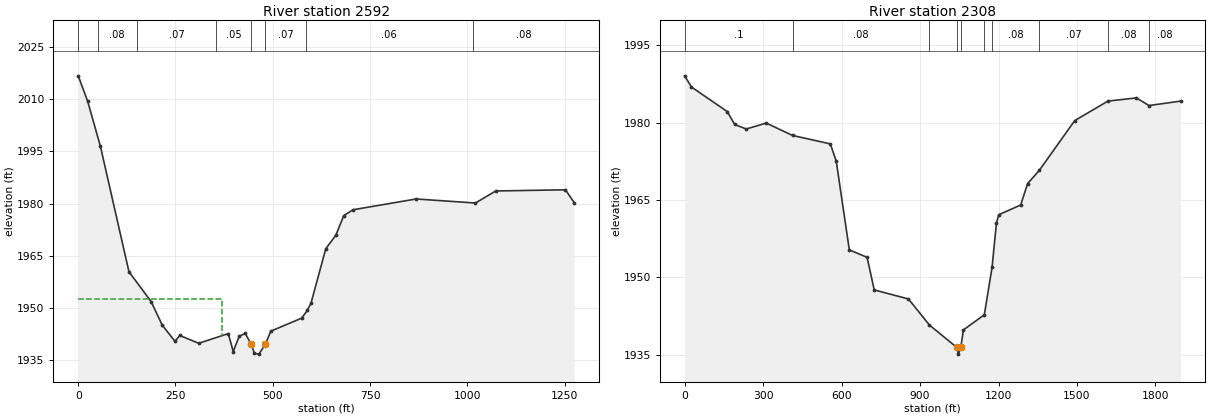
Type RM Length L Ch R = 1 ,2592    ,278.9,283.6,290.8
XS GIS Cut Line= 4
2292564.87019554678117.3105932272292501.72650588678435.774419329
 2292751.5558867678844.8357132012292718.61135297 679314.29531892
#Sta/Elev= 30
       0 2016.73    24.3  2009.4      57 1996.48   130.4 1960.39   187.4 1951.79
     216 1945.01   248.9 1940.33   260.8 1942.06   309.8 1939.79   385.7 1942.59
   398.4 1937.43   413.8 1941.82   429.4 1942.64   444.5 1939.52   452.9 1936.91
   464.2 1936.68     481 1939.48     495 1943.29   574.4 1947.04   588.8 1949.26
   598.2 1951.31   636.3 1967.01   662.1 1970.87   682.5 1976.51     706  1978.2
   868.5 1981.31  1020.9 1980.14    1073 1983.61  1252.3 1983.95  1274.6 1980.28
#Mann= 8 ,-1,0
       0      .1       0      50     .08       0     150     .07       0
  354.66     .05       0   444.5    .045       0     481     .07       0
  584.66     .06       0 1013.98     .08       0
#XS Ineff= 2 , 0
          370.54 1952.58
Permanent Ineff=
       F       F
Bank Sta=444.5,481
XS Rating Curve= 0 ,0
Exp/Cntr(USF)=0,0
Exp/Cntr=0.3,0.1

Type RM Length L Ch R = 1 ,2308    ,186.8,184,182.6
XS GIS Cut Line= 3
2292099.09854734677575.3242065742292047.16774327 678027.30167345
2292726.87494018679298.262312503
#Sta/Elev= 30
       0 1989.09    25.6 1986.93   162.9 1982.16   191.1 1979.66   235.4 1978.78
   311.9 1979.93   412.4 1977.53   556.9  1975.9   579.6 1972.52   629.5 1955.35
   697.5  1953.9   724.7 1947.59   855.7 1945.83   935.9 1940.77  1039.3 1936.49
  1046.8 1935.14  1055.8 1936.53  1065.9 1939.84  1145.7 1942.77  1175.3 1951.96
  1191.9 1960.52    1201 1962.16  1284.6 1964.05  1311.2  1968.2  1356.2 1970.78
  1491.3 1980.41  1618.3 1984.19  1727.2 1984.81  1775.2 1983.33  1896.2 1984.19
#Mann= 10 ,-1,0
       0      .1       0   412.4     .08       0   935.9     .07       0
  1039.3    .045       0  1055.8     .08       0  1145.7     .07       0
  1175.3     .08       0  1356.2     .07       0  1618.3     .08       0
  1775.2     .08       0
Bank Sta=1039.3,1055.8
XS Rating Curve= 0 ,0
Exp/Cntr(USF)=0,0
Exp/Cntr=0.3,0.1