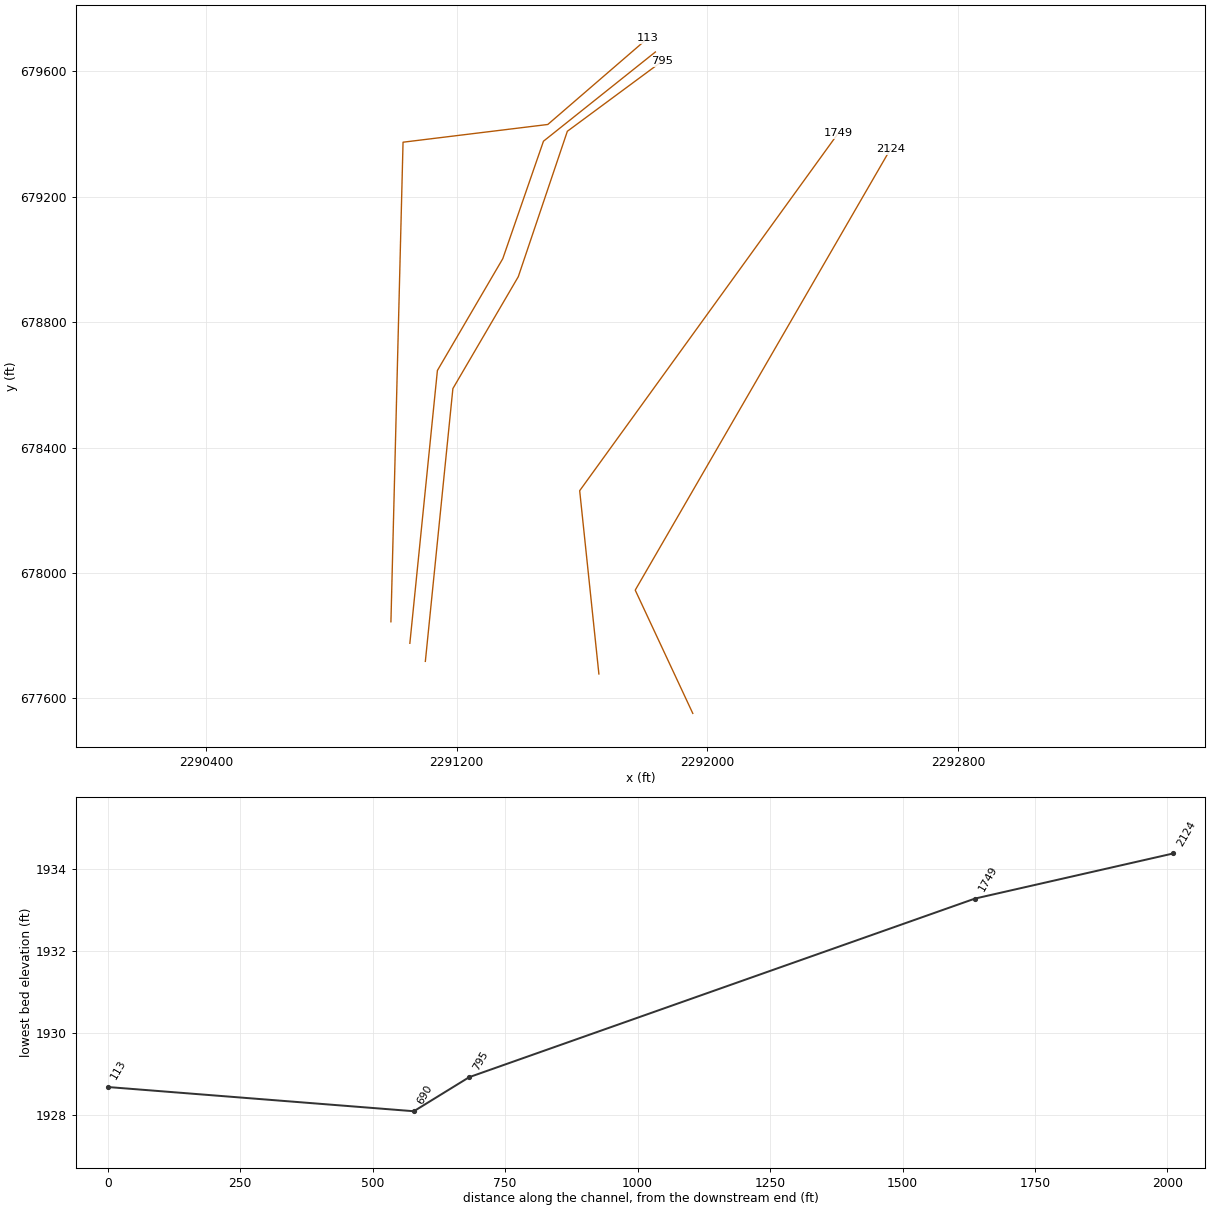
HEC-RAS study KINGSRN.prj: KINGSRN

--- KINGSRN.g01 (geometry) --- (continued)

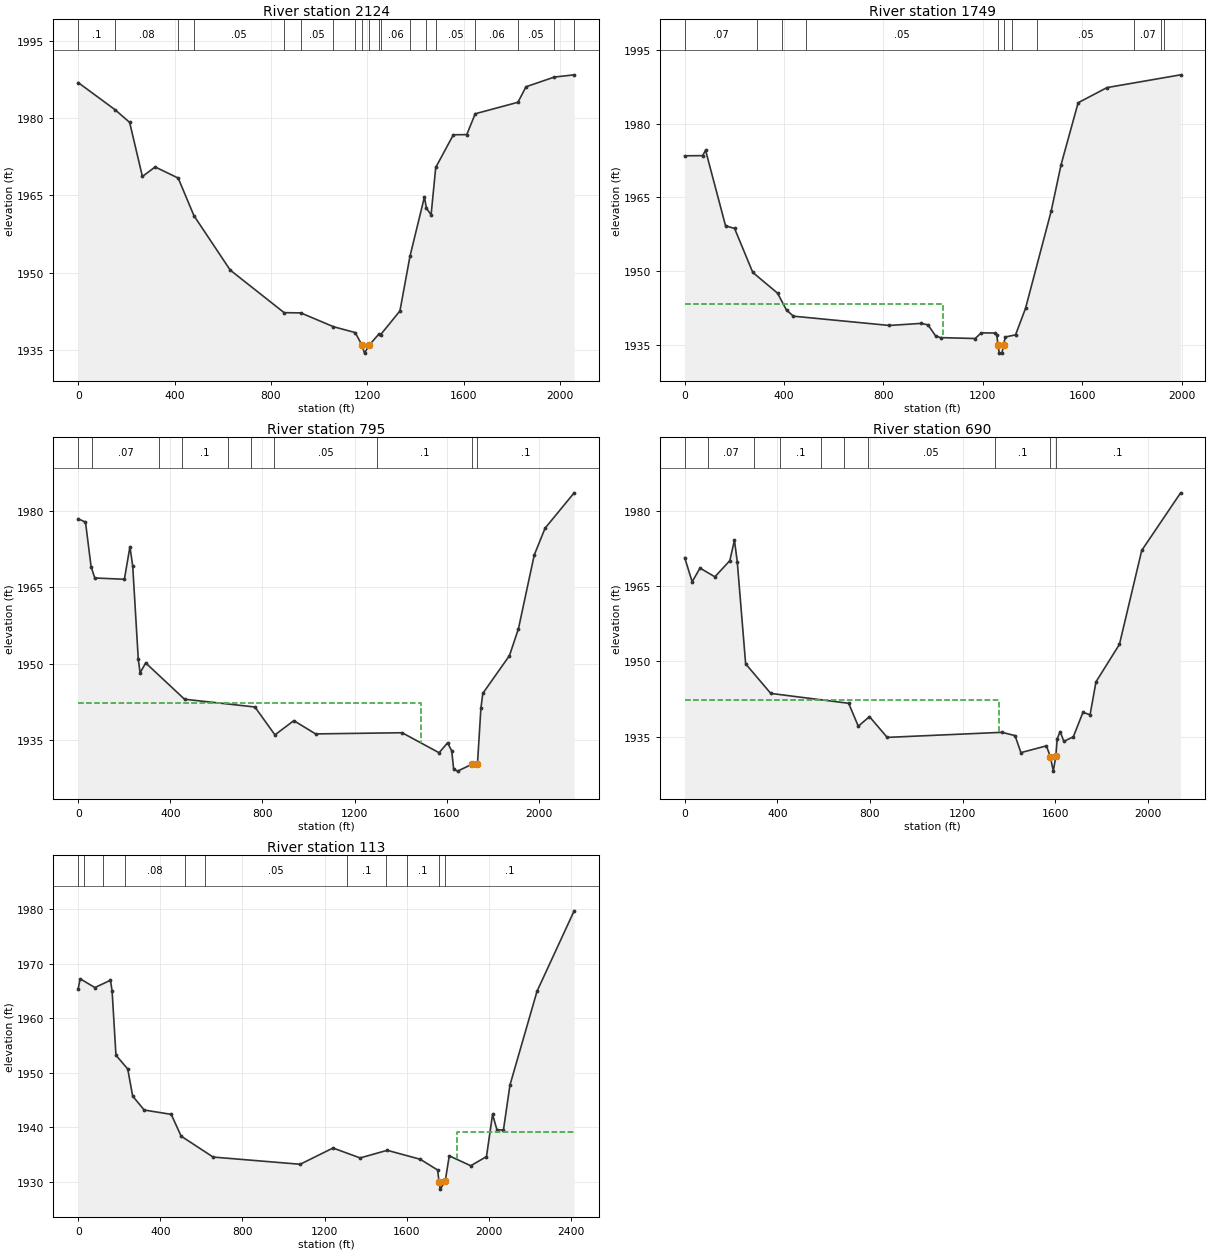
Type RM Length L Ch R = 1 ,2124    ,373,374.5,363.2
XS GIS Cut Line= 3
2291953.20917046677551.7627641142291769.57954236677944.940339114
2292583.31913443679351.138289147
#Sta/Elev= 30
       0 1986.91   153.7 1981.62   213.5 1979.18   266.4 1968.68   319.4 1970.53
     415 1968.37   480.4 1961.07   630.8 1950.51   854.8 1942.24   924.1 1942.19
  1059.6 1939.51  1149.9 1938.37 1176.581936.037  1188.4 1934.38 1208.811935.999
  1247.6 1938.05  1255.7 1937.99  1335.4 1942.57    1377 1953.16  1437.1  1964.7
  1445.4 1962.52  1464.8 1961.23    1484 1970.43  1557.2 1976.78  1612.8 1976.81
    1648 1980.86  1825.3 1983.09  1858.7  1986.1  1975.8 1987.98  2058.6 1988.42
#Mann= 19 ,-1,0
       0      .1       0   153.7     .08       0     415     .06       0
   480.4     .05       0   854.8     .07       0   924.1     .05       0
  1059.6     .07       0  1149.9     .05       0 1176.58    .045       0
 1208.81     .05       0  1247.6     .07       0  1255.7     .06       0
    1377     .05       0  1445.4     .07       0    1484     .05       0
    1648     .06       0  1825.3     .05       0  1975.8     .07       0
  2058.6     .06       0
Bank Sta=1176.58,1208.81
XS Rating Curve= 0 ,0
Exp/Cntr(USF)=0,0
Exp/Cntr=0.3,0.1

Type RM Length L Ch R = 1 ,1749    ,955.6,954.6,947.4
XS GIS Cut Line= 3
2291653.66359033677677.5202041682291592.39794246678262.156204586
2292417.78946703 679403.43227281
#Sta/Elev= 30
       0  1973.5    72.1 1973.53    84.1 1974.62   164.6 1959.22   200.8  1958.7
   274.1 1949.73   373.7 1945.51   409.9 1942.04     438 1940.81   823.6 1938.92
   951.9 1939.34   979.4 1939.04  1010.6 1936.75  1030.4 1936.44  1169.1 1936.26
  1193.8 1937.41  1248.1 1937.38  1256.4    1937 1260.94 1934.93  1265.9  1933.4
  1276.9 1933.28  1283.7 1934.99  1290.5 1936.57  1331.8    1937  1371.9 1942.39
  1475.2 1962.21  1515.1 1971.69  1583.8 1984.31    1700  1987.4  1996.3    1990
#Mann= 11 ,-1,0
       0     .07       0     290     .08       0     390     .06       0
     490     .05       0 1260.94    .045       0  1283.7     .05       0
 1317.84      .1       0 1417.84     .05       0 1807.84     .07       0
 1917.84     .06       0 1927.84     .08       0
#XS Ineff= 2 , 0
         1040.97 1943.37
Permanent Ineff=
       F       F
Bank Sta=1260.94,1283.7
XS Rating Curve= 0 ,0
Exp/Cntr(USF)=0,0
Exp/Cntr=0.3,0.1

Type RM Length L Ch R = 1 ,795     ,113.3,104.5,113.2
XS GIS Cut Line= 5
2291100.00811764677717.696446055 2291187.8602076678587.981212213
2291396.50892126678944.880327672 2291552.9954565 679408.84917777
2291855.26155351679632.213116491
#Sta/Elev= 30
       0 1978.41    31.6 1977.77    55.8 1969.06    71.8 1966.81   200.5 1966.56
   224.6 1972.95   236.7 1969.15   260.8 1950.88   268.8 1948.21     293 1950.15
   461.8 1943.03   767.4 1941.51   854.2 1936.04   936.3 1938.83  1030.8 1936.23
  1406.6 1936.46    1567 1932.54  1603.8 1934.47  1621.9 1932.93  1630.4 1929.29
  1647.3 1928.93  1709.5 1930.27 1733.711930.285  1748.6 1941.24    1757 1944.18
  1872.6 1951.58  1911.8 1956.88  1980.2  1971.3  2027.4 1976.58  2153.6 1983.51
#Mann= 10 ,-1,0
       0     .06       0      60     .07       0     350     .08       0
     450      .1       0     650     .08       0     750     .07       0
     850     .05       0 1298.12      .1       0  1709.5    .045       0
 1733.71      .1       0
#XS Ineff= 2 , 0
         1486.71 1942.28
Permanent Ineff=
       F       F
Bank Sta=1709.5,1733.71
XS Rating Curve= 0 ,0
Exp/Cntr(USF)=0,0
Exp/Cntr=0.3,0.1

Type RM Length L Ch R = 1 ,690     ,586.5,577.7,560.8
XS GIS Cut Line= 5
2291050.59131704 677775.34938009  2291138.443407678645.634146249
2291347.09212065679002.5332617082291476.83867601679377.175753962
2291833.86407885679661.846724585
#Sta/Elev= 30
       0 1970.69    32.3 1965.87    66.2  1968.6   130.5 1966.86   194.8 1970.08
   214.9 1974.16     227 1969.88   263.2  1949.5   371.7  1943.6   707.9 1941.63
   749.6 1937.06   797.9 1938.97   874.3 1934.83  1369.7 1935.84  1426.3 1935.18
  1451.8 1931.79  1561.8 1933.14  1578.8 1930.98  1591.5  1928.1 1602.361931.031
  1608.4 1934.57  1621.1 1935.99  1636.9 1934.05  1677.8 1934.93  1719.6 1939.83
  1750.3 1939.34  1775.8 1945.91  1877.1 1953.39  1973.3 1972.12  2141.2 1983.61
#Mann= 10 ,-1,0
       0     .08       0     100     .07       0     300     .08       0
     410      .1       0     590     .08       0     690     .07       0
     790     .05       0 1338.12      .1       0  1578.8    .045       0
 1602.36      .1       0
#XS Ineff= 2 , 0
         1356.59 1942.28
Permanent Ineff=
       F       F
Bank Sta=1578.8,1602.36
XS Rating Curve= 0 ,0
Exp/Cntr(USF)=0,0
Exp/Cntr=0.3,0.1

Type RM Length L Ch R = 1 ,113     ,,,
XS GIS Cut Line= 4
2290990.19300519677843.9838253712291028.85890629679374.024060234
 2291490.6580077679430.5881944522291809.06782646 679705.40214356
#Sta/Elev= 30
       0 1965.43     9.2 1967.27    81.3 1965.66   157.2    1967   165.2 1964.99
   183.9 1953.25   241.3 1950.72   265.3 1945.76   321.3  1943.2   453.3  1942.4
   501.4 1938.41   657.4 1934.57  1081.5 1933.25  1241.6 1936.23  1373.6 1934.41
  1505.7 1935.81  1666.9 1934.16  1751.1  1932.2 1758.081930.078  1763.6 1928.69
  1787.8  1930.1  1807.9 1934.79  1912.7 1932.98  1989.2 1934.66  2018.9  1942.4
  2040.1 1939.59  2071.8 1939.51  2103.6 1947.77  2235.6 1964.99  2416.4 1979.73
#Mann= 11 ,-1,0
       0     .07       0      30     .08       0     120     .07       0
     230     .08       0     520     .06       0     620     .05       0
    1310      .1       0    1500    .025       0 1600.53      .1       0
 1758.08    .045       0  1787.8      .1       0
#XS Ineff= 2 , 0
                         1843.85          1939.1
Permanent Ineff=
       F       F
Bank Sta=1758.08,1787.8
XS Rating Curve= 0 ,0
Exp/Cntr(USF)=0,0
Exp/Cntr=0.3,0.1
LCMann Table=0

Chan Stop Cuts=-1
Use User Specified Reach Order=0
Composite Channel Slope=5